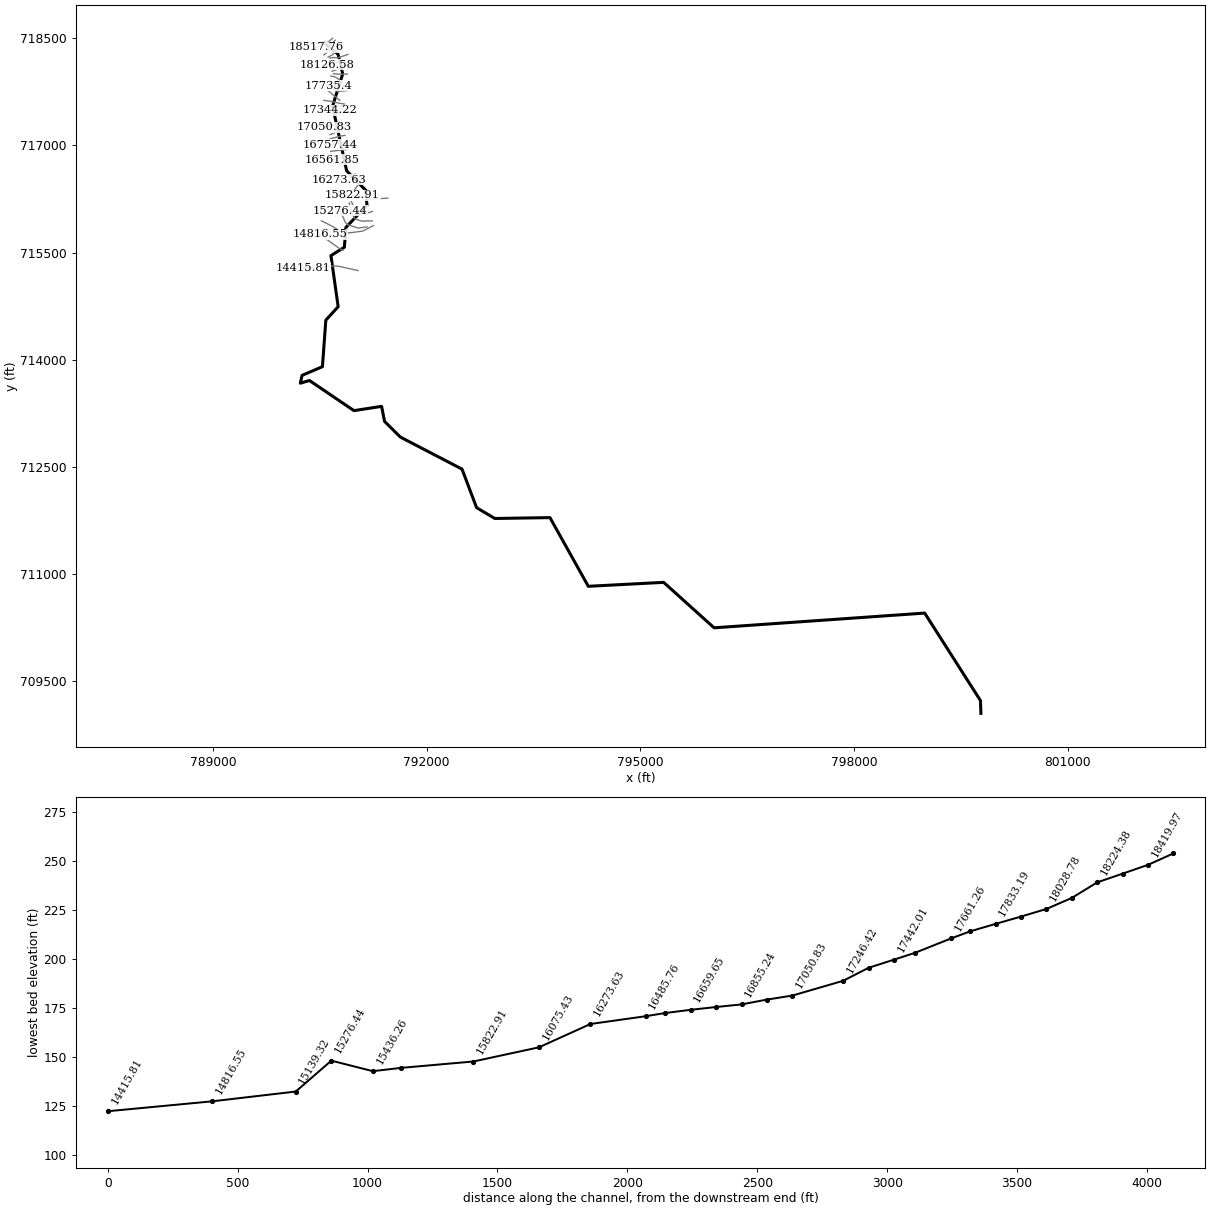
--- 6662_ras.prj (project) ---

Proj Title=6662
Current Plan=p01
Default Exp/Contr=0.3,0.1
English Units
Geom File=g01
Flow File=f01
Plan File=p01
Y Axis Title=Elevation
X Axis Title(PF)=Main Channel Distance
X Axis Title(XS)=Station
BEGIN DESCRIPTION:
RFD model 6662 exported to HEC-RAS
END DESCRIPTION:

--- 6662_ras.p01 (plan) ---

Plan Title=Plan 01
Program Version=4.10
Short Identifier=Plan 01
Geom File=g01
Flow File=f01
Subcritical Flow
Calc Critical at every XS
Secant Critical Depth

--- 6662_ras.f01 (steady flow) ---

Flow Title=Flow 01
Program Version=5.01
Number of Profiles= 6
Profile Names=10yr,25yr,50yr,100yr,100plus,500yr
River Rch & RM=6662,62,18517.76
   95.95  171.37  248.46   328.4  479.47 1012.27
River Rch & RM=6662,62,17833.19
   97.32  173.84  252.04  333.14  486.39 1024.82
River Rch & RM=6662,62, 17735.4
   98.11  175.27  254.14  335.93  490.46 1032.31
River Rch & RM=6662,62,17523.76
   100.2  179.06  259.69  343.33  501.27  1052.2
River Rch & RM=6662,62,17442.01
   108.1  193.44  280.83  371.56  542.48 1127.94
River Rch & RM=6662,62,17344.22
  110.15  197.16  286.27  378.82  553.08 1147.15
River Rch & RM=6662,62,17050.83
  120.96  216.92   315.4  417.81     610  1250.7
River Rch & RM=6662,62,16855.24
  123.37  221.34  321.91  426.54  622.75 1273.76
River Rch & RM=6662,62,16757.44
  124.86  224.05  325.88  431.83  630.47 1287.52
River Rch & RM=6662,62,16659.65
  126.11  226.31   329.2  436.24  636.92 1298.94
River Rch & RM=6662,62,16561.85
  127.57  228.97  333.11  441.48  644.56  1312.6
River Rch & RM=6662,62,16273.63
   279.4  503.28   734.4   974.8  1423.2 2597.97
River Rch & RM=6662,62,16075.43
  280.44  505.17  737.19  978.52 1428.65 2606.64
River Rch & RM=6662,62,15822.91
  281.24  506.65  739.37  981.47 1432.94 2613.58
River Rch & RM=6662,62, 15543.9
  285.97   515.4  752.37  998.98 1458.51 2655.04
River Rch & RM=6662,62,15436.26
  287.34  517.94  756.16 1004.07 1465.94 2667.08
River Rch & RM=6662,62,15276.44
  288.52  520.12  759.39 1008.43 1472.31 2677.39
River Rch & RM=6662,62,15139.32
  337.43  610.18  892.79 1187.63 1733.94  3092.5
River Rch & RM=6662,62,14816.55
  341.67  618.08   904.6  1203.6 1757.26 3129.72
River Rch & RM=6662,62,14415.81
  345.87  625.93  916.34  1219.5 1780.47 3166.76
River Rch & RM=6662,62,14174.63
  362.88  657.45  963.22  1282.7 1872.75  3311.7
River Rch & RM=6662,62,13933.46
  364.54  660.52   967.8 1288.89 1881.78  3325.9
River Rch & RM=6662,62,13699.06
  365.75  662.81  971.25 1293.59 1888.65 3336.92
River Rch & RM=6662,62, 13630.6
  366.26  663.79  972.72  1295.6 1891.58 3341.64
River Rch & RM=6662,62,13428.34
  401.34  728.89 1069.67 1426.42 2082.57 3638.63
River Rch & RM=6662,62,13186.17
  404.86  735.55 1079.73 1440.16 2102.63 3670.53
River Rch & RM=6662,62,12943.99
  406.54  738.73 1084.53  1446.7 2112.19 3685.68
River Rch & RM=6662,62,12554.59
  454.31  828.73 1219.84 1630.84 2381.02 4104.95
River Rch & RM=6662,62,11975.29
  457.39  834.58 1228.68 1642.91 2398.66 4132.49
River Rch & RM=6662,62,11733.11
  463.91  847.03 1247.54 1668.76 2436.38 4191.67
River Rch & RM=6662,62,11490.94
  466.71  852.32  1255.5  1679.6 2452.22 4216.11
River Rch & RM=6662,62, 10816.1
  477.27  872.22 1285.44 1720.35 2511.71 4307.62
River Rch & RM=6662,62,10522.24
  704.55 1308.17 1948.69 2632.14 3842.92  6332.9
River Rch & RM=6662,62,10280.06
  706.78 1312.39 1955.05 2640.82 3855.59 6351.25
River Rch & RM=6662,62,10006.54
  769.76 1430.28 2131.75 2880.45 4205.45 6847.46
River Rch & RM=6662,62,9388.892
  780.65 1450.51 2161.94 2921.21 4264.96 6930.35
River Rch & RM=6662,62,9148.389
  783.07 1455.04 2168.73 2930.42 4278.41 6949.24
River Rch & RM=6662,62,8907.886
  797.34 1481.94 2209.22 2985.53 4358.87 7063.35
River Rch & RM=6662,62,8667.383
  865.47 1606.85 2393.95  3232.9 4720.04  7550.5
River Rch & RM=6662,62, 8194.88
  886.51 1646.36  2453.3 3313.55 4837.78 7714.29
River Rch & RM=6662,62,7826.645
  890.47 1653.72 2464.27 3328.35 4859.39 7743.72
River Rch & RM=6662,62,7249.873
 1041.45 1928.84 2869.54 3868.93 5648.64 8776.01
River Rch & RM=6662,62,6707.912
 1044.31 1934.14  2877.4 3879.51 5664.09 8796.46
River Rch & RM=6662,62, 5359.86
 1170.69 2171.89 3235.04 4365.76 6374.01 9754.28
River Rch & RM=6662,62,4887.357
 1174.28  2178.5 3244.83  4378.9  6393.2 9779.06
River Rch & RM=6662,62,4666.207
 1175.47 2180.69 3248.08 4383.26 6399.57 9787.32
River Rch & RM=6662,62,3829.429
 1332.36  2467.4 3671.31  4948.7  7225.110832.53
River Rch & RM=6662,62,2991.838
 1340.13 2481.61 3692.29 4976.76 7266.0610884.03
River Rch & RM=6662,62,1973.384
 1356.05 2510.61 3735.02 5033.73 7349.2410987.73
River Rch & RM=6662,62,1357.048
 1512.41 2793.81 4150.65 5585.88 8155.3811975.12
River Rch & RM=6662,62,718.2181
 1517.97 2803.99 4165.68 5605.95 8184.6912011.31
River Rch & RM=6662,62,       0
 1532.96 2831.34 4206.04 5659.86 8263.3912108.25
Boundary for River Rch & Prof#=6662,62,1
Up Type= 0
Dn Type= 2
Boundary for River Rch & Prof#=6662,62,2
Up Type= 0
Dn Type= 2
Boundary for River Rch & Prof#=6662,62,2
Up Type= 0
Dn Type= 2
Boundary for River Rch & Prof#=6662,62,2
Up Type= 0
Dn Type= 2
Boundary for River Rch & Prof#=6662,62,2
Up Type= 0
Dn Type= 2
Boundary for River Rch & Prof#=6662,62,2
Up Type= 0
Dn Type= 2

--- 6662_ras.g01 (geometry) ---

Geom Title=6662
Program Version=4.10

River Reach=6662,62
Reach XY= 30
790572.493874401718427.863441855790756.807728857718278.240226433
 790822.95040977718001.335687548790680.430367023717549.916621223
790878.239778996 716644.44831261791148.300784439716370.254115343
791162.959363103716162.041225448790867.629245877715853.036032036
790846.217451096715575.983282015790657.919620544715457.803033724
790758.957737654714743.053077742790585.836670727714554.697484896
790538.346997499 713903.78549026790252.642231315713782.397097707
790227.809216201713672.504849955790355.955939829713710.229910821
  790980.7660622713288.656893104791368.786895573713348.552726462
791410.073638707713138.560532615791631.807728857712918.865226433
792497.487783939 712470.29023312 792702.22439909711930.782690451
792957.927902192711779.353603899793732.202104479  711791.3670789
794270.314201534710830.237060472795328.085370332710885.261679813
796036.253362536710249.101270869798992.050784469710455.323559776
799775.431269288709229.822075337799781.113284439709051.677726433

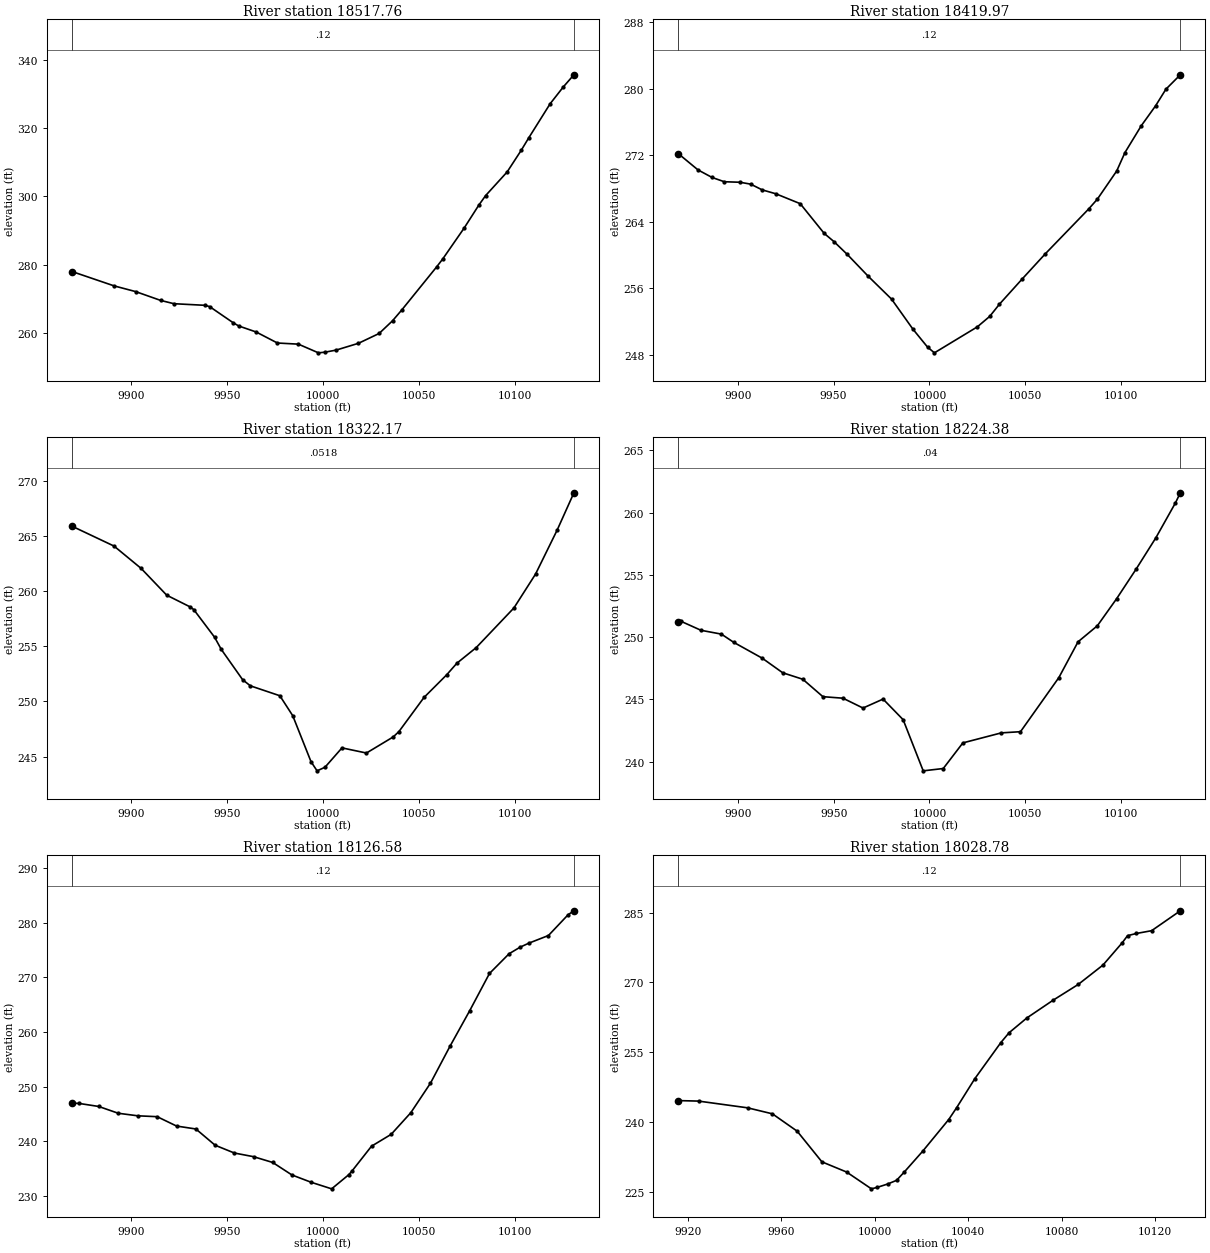
Type RM Length L Ch R = 1 ,18517.76,97.795400,97.795400,97.795400
XS GIS Cut Line= 6
790680.433899035718499.100519826790630.818626037718457.608079262
790604.678587866718439.587506318790587.269007644718431.332365425
790534.020446307718413.221705306  790453.9394497718372.539312276
#Sta/Elev= 30
9869.107277.94439891.087273.72819902.263272.06149915.299269.47179922.263268.4999
9938.381268.03019940.853267.65979952.999262.96799955.999261.97019965.145260.1908
9976.243256.95289987.178256.61719997.646254.0651   10001254.253410006.86254.8673
10018.53256.869910029.29259.750210036.28 263.474 10041.1266.648610059.26279.2861
10062.44281.608210073.65 290.71910081.34297.487610084.87300.269710096.09307.2117
10103.41313.5456 10107.3317.173410118.52327.246410125.49332.257310130.93335.7614
#Mann= 3 , 0 , 0
9869.107    0.12       09869.107    0.12       010130.93    0.12       0
#XS Ineff= 2 , 0
       0                               0
Bank Sta=9869.107,10130.93
Exp/Cntr=0.3,0.1

Type RM Length L Ch R = 1 ,18419.97,97.795500,97.795500,97.795500
XS GIS Cut Line= 6
790717.028418179718472.416589292790664.242639299718410.938034456
790626.232659885718339.218281961790610.367573456718315.106749754
790585.926843106718288.428062899790559.125897101 718266.91343386
#Sta/Elev= 30
9869.094272.18939879.276270.24729886.649269.33439893.006268.82269901.243268.7596
9906.735 268.5349912.761267.84259919.844267.37559932.598  266.189945.094262.6032
9950.222261.60819957.151260.06729968.154257.41829980.212254.69629991.383 251.069
    9999248.910810002.59248.219610024.97251.347810031.44252.610510036.49254.0733
10048.46 257.13610060.45260.149210083.05265.543810087.57266.722510097.67270.1178
10101.96272.3326 10110.5 275.57110117.94 277.96110123.32279.961710130.85281.7018
#Mann= 3 , 0 , 0
9869.094    0.12       09869.094    0.12       010130.85    0.12       0
#XS Ineff= 2 , 0
       0                               0
Bank Sta=9869.094,10130.85
Exp/Cntr=0.3,0.1

Type RM Length L Ch R = 1 ,18322.17,97.795500,97.795500,97.795500
XS GIS Cut Line= 6
790811.348571585718407.034432675790757.309286642718355.988300082
790708.752910228718296.947830122790693.656831953718281.491796793
790662.463058612718259.121525575 790617.21602068718235.672609644
#Sta/Elev= 27
9869.065265.88819890.961264.08799905.078262.06529918.441259.63629930.674258.5728
9932.567258.32539943.432255.8201 9946.93 254.7139958.062251.96969962.076251.4188
9977.452250.52069984.188 248.709 9993.71244.54379996.871243.7127   10001244.0382
10009.87245.794110022.63245.3269 10036.6246.787510039.59247.276110052.65250.3635
10064.47252.415110069.81253.469410079.89254.885310099.56258.479310110.83261.5458
10122.09265.528510130.86  268.92
#Mann= 3 , 0 , 0
9869.065  0.0518       09869.065  0.0518       010130.86  0.0518       0
#XS Ineff= 2 , 0
       0                               0
Bank Sta=9869.065,10130.86
Exp/Cntr=0.3,0.1

Type RM Length L Ch R = 1 ,18224.38,97.795500,97.795500,97.795500
XS GIS Cut Line= 6
790896.001534395718274.983239417790842.890498561718255.400583739
790759.665088854718229.859745799790743.815203576718228.527252059
790693.060753809718230.747934278790642.519619658 718221.81574449
#Sta/Elev= 26
9869.066 251.2469870.133251.28489880.791250.54649891.449250.23829897.924249.5742
9912.765248.30289923.424247.1324 9933.93246.60969944.395245.21149954.861245.0883
9965.326244.29759975.792 245.0179986.257243.36069996.723239.250910007.18239.4368
10017.41241.496510037.46242.301610047.47242.396410067.49246.7474 10077.5249.6215
10087.55250.906410097.62253.085410107.78255.460810118.04257.9684 10128.3260.7854
10130.84261.5964
#Mann= 3 , 0 , 0
9869.066    0.04       09869.066    0.04       010130.84    0.04       0
#XS Ineff= 2 , 0
       0                               0
Bank Sta=9869.066,10130.84
Exp/Cntr=0.3,0.1

Type RM Length L Ch R = 1 ,18126.58,97.795500,97.795500,97.795500
XS GIS Cut Line= 6
790858.614037842718173.176247921790792.029316251718161.814969119
790769.829834711718160.666057137790735.270804141 718161.54488828
790714.801664357 718154.43031319790602.058022971718128.794332597
#Sta/Elev= 30
9869.172246.98739872.857246.92779883.056246.37449893.255245.12999903.454244.6621
9913.561244.50149923.656242.78729933.751242.24859943.788239.27189953.802237.8461
 9963.81237.17739973.813236.11539983.817233.83049993.832232.493410004.55231.2855
10013.46233.866910015.08234.508810025.34239.093810035.59 241.26610045.85245.2345
 10056.1250.640810066.36257.459210076.61263.950210086.87270.734910097.12274.3542
10102.92275.563510107.38276.282110117.63277.689710127.89 281.49710130.91 282.218
#Mann= 3 , 0 , 0
9869.172    0.12       09869.172    0.12       010130.91    0.12       0
#XS Ineff= 2 , 0
       0                               0
Bank Sta=9869.172,10130.91
Exp/Cntr=0.3,0.1

Type RM Length L Ch R = 1 ,18028.78,97.795500,97.795500,97.795500
XS GIS Cut Line= 6
790873.297219634718116.571949458790857.273111847718112.213546154
790788.435933819718088.167473961 790721.83939862718055.050293733
790697.178387417 718046.43150858790673.065387362718040.482610032
#Sta/Elev= 27
9916.002 244.6029924.601244.49419945.615243.04679956.212241.7596 9966.81238.0323
9977.407231.44249988.005229.24599998.602225.6397   10001225.943310005.53226.6709
10009.36227.461610012.64229.233810020.53233.7078 10031.7240.5333 10035.1243.0851
10042.87249.306210054.04257.083310057.56259.1904 10065.2262.377310076.37266.1651
10087.15269.561310097.74273.726310106.03278.545610108.27280.0428   10112280.5093
10118.57281.111710130.86285.3913
#Mann= 3 , 0 , 0
9916.002    0.12       09916.002    0.12       010130.86    0.12       0
#XS Ineff= 2 , 0
       0                               0
Bank Sta=9916.002,10130.86
Exp/Cntr=0.3,0.1

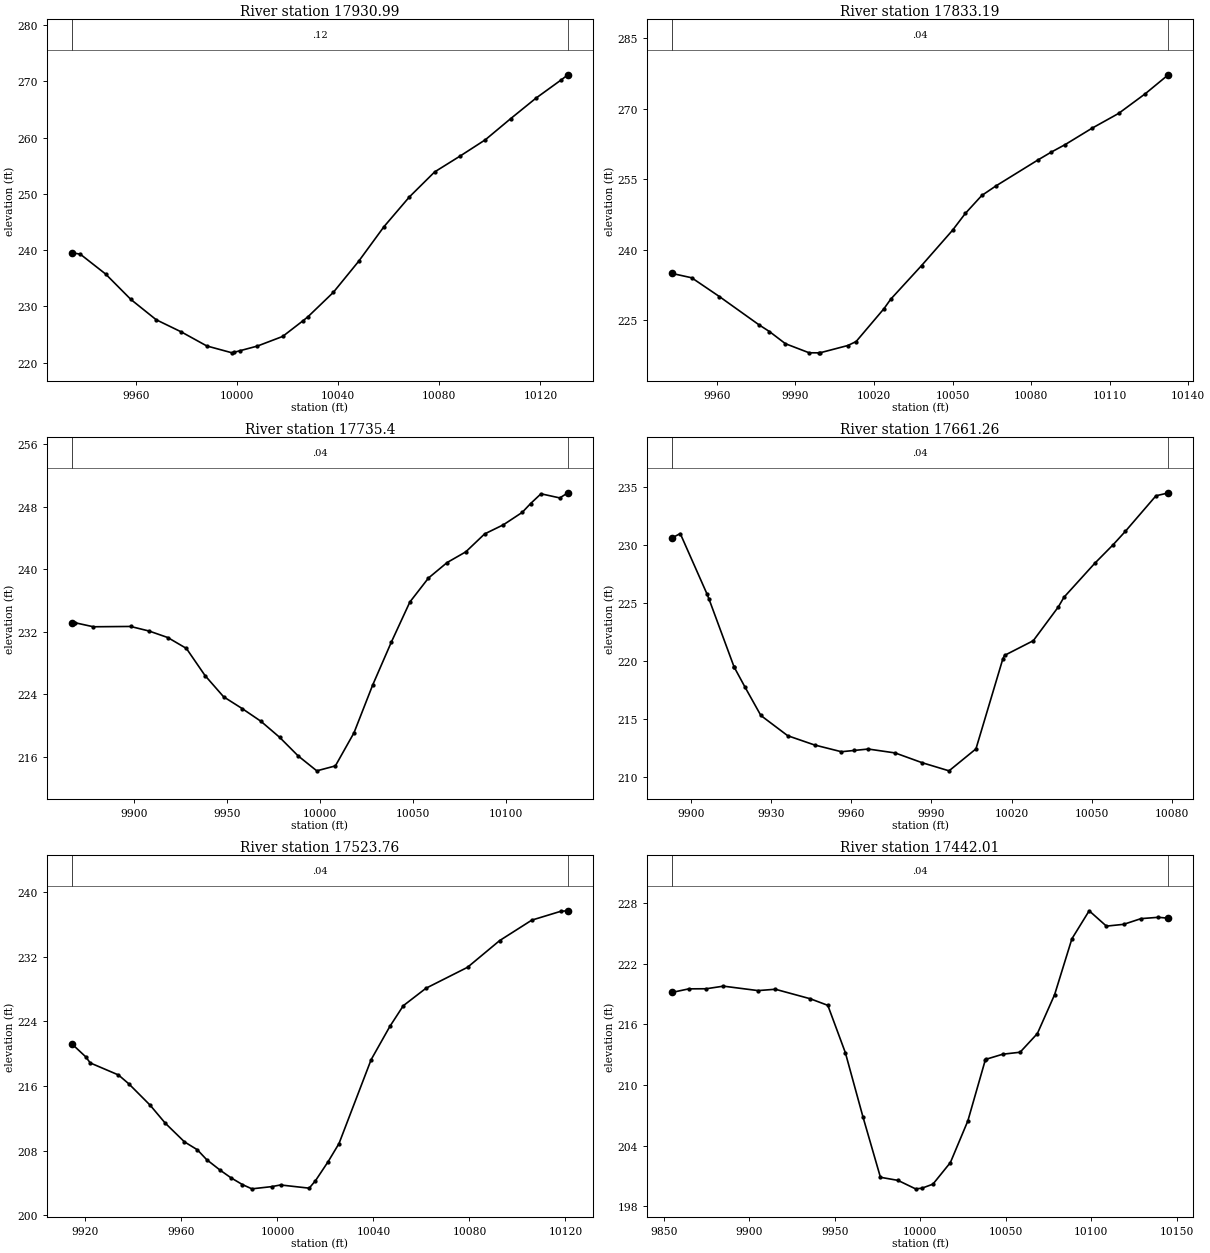
Type RM Length L Ch R = 1 ,17930.99,97.795500,97.795500,97.795500
XS GIS Cut Line= 5
790888.418438221717999.454301253790824.048399611717996.998514595
790822.048907221717996.953457045790796.910143216  717995.9581362
790692.410765183 718003.20948254
#Sta/Elev= 25
9934.583239.55249938.004239.28319948.011235.76149958.019231.23659968.026227.6353
9978.033225.4559 9988.04222.97879998.048 221.755    9999221.8696   10001222.1113
10008.05222.956910018.06224.668610026.16 227.47510028.07228.1666 10038.1   232.5
10048.12238.018510058.15244.178810068.17249.446910078.19 253.90210088.22256.7086
10098.24259.613810108.27263.370210118.29267.016210128.31  270.2710130.91271.1623
#Mann= 3 , 0 , 0
9934.583    0.12       09934.583    0.12       010130.91    0.12       0
#XS Ineff= 2 , 0
       0                               0
Bank Sta=9934.583,10130.91
Exp/Cntr=0.3,0.1

Type RM Length L Ch R = 1 ,17833.19,97.795500,97.795500,97.795500
XS GIS Cut Line= 6
790821.725194903717886.555148399790792.553506286717902.405901781
790757.134020147 717934.33763641790730.880241925 717950.84239472
790700.148800418 717962.55495013790656.370448401717971.125846881
#Sta/Elev= 25
9942.919234.91939950.424233.9939 9961.02229.98769976.159  223.969980.093222.5507
9986.208219.95469995.256218.0191    9999218.00879999.553218.036910010.02219.5679
10013.19220.411910023.86227.435510026.38229.417810038.19236.6027   10050244.1147
10054.87247.688710061.16251.517410066.54253.546410082.56259.070610087.75260.7759
   10093262.358810103.19265.827210113.38268.989210123.57273.184110132.36277.2273
#Mann= 3 , 0 , 0
9942.919    0.04       09942.919    0.04       010132.36    0.04       0
#XS Ineff= 2 , 0
       0                               0
Bank Sta=9942.919,10132.36
Exp/Cntr=0.3,0.1

Type RM Length L Ch R = 1 , 17735.4,74.140900,74.140900,74.140900
XS GIS Cut Line= 6
790886.674264169717830.811712163790832.422338065717831.563679735
790755.967775761717827.031927005790718.971515121717826.595720328
790675.295670819717829.829747411790620.681821209717837.948837892
#Sta/Elev= 29
9866.568233.15389868.242233.17279878.243232.65059898.245232.69129908.246232.1021
9918.247231.2739 9928.26229.88069938.278226.41079948.295223.68729958.313222.1754
9968.331220.55859978.348218.51669988.366216.12579998.382214.216510008.38214.8485
10018.39219.085110028.39225.1704 10038.4230.649810048.42235.813210058.45238.8907
10068.48240.871310078.51242.237710088.62244.528510098.73 245.70110108.84247.2848
10113.37248.420210118.95249.664810129.06249.136710133.42249.7954
#Mann= 3 , 0 , 0
9866.568    0.04       09866.568    0.04       010133.42    0.04       0
#XS Ineff= 2 , 0
       0                               0
Bank Sta=9866.568,10133.42
Exp/Cntr=0.3,0.1

Type RM Length L Ch R = 1 ,17661.26,137.499200,137.499200,137.499200
XS GIS Cut Line= 6
790878.068837911717766.890267596790864.211425841717766.783370405
790854.930356413717765.320289508790810.360504568717761.681934252
790754.370921254717755.171517581790700.985504568717785.119434252
#Sta/Elev= 28
9893.001230.6293 9896.07231.00749906.071225.79939906.859225.33719916.184219.5163
9916.255219.48469920.191217.80529926.218215.31849936.251213.57489946.285212.7764
9956.318212.19419960.973212.3009 9966.37212.42679976.437 212.0899986.504211.2484
9996.572210.546210006.64212.439510016.71220.214110017.34220.503110028.08221.7684
10037.43224.677510039.55225.514710051.02228.430910057.87230.027810062.48231.1921
10073.95234.264710078.31234.496410078.55234.5229
#Mann= 3 , 0 , 0
9893.001    0.04       09893.001    0.04       010078.55    0.04       0
#XS Ineff= 2 , 0
       0                               0
Bank Sta=9893.001,10078.55
Exp/Cntr=0.3,0.1

Type RM Length L Ch R = 1 ,17523.76,81.746400,81.746400,81.746400
XS GIS Cut Line= 6
790781.606164306717631.943797663790751.007257909717654.215545952
790728.329254597717678.348600924790698.381337941717697.879850909
790629.208126634717759.487242267790622.189885974717761.493142381
#Sta/Elev= 29
9914.235221.23469920.074219.61469921.988218.85019933.739217.36059938.076216.2582
9946.934213.6181 9953.25211.3875 9961.26209.07079966.611208.09569970.484206.8764
9976.146205.56079980.533204.64329985.377203.78589989.352203.25439997.553203.5268
10001.29203.733910013.23203.337510015.86204.266210021.13206.624710025.66208.8673
10039.05219.259510046.87223.383210052.44225.935410061.91 228.10410079.22230.6979
10092.61234.007310106.01236.541410118.14  237.6410121.06237.6993
#Mann= 3 , 0 , 0
9914.235    0.04       09914.235    0.04       010121.06    0.04       0
#XS Ineff= 2 , 0
       0                               0
Bank Sta=9914.235,10121.06
Exp/Cntr=0.3,0.1

Type RM Length L Ch R = 1 ,17442.01,97.795500,97.795500,97.795500
XS GIS Cut Line= 6
790844.725077436717579.800907167790779.589035087717589.797064877
790703.330647034717607.242999199790701.344756216717607.480144006
790648.844303697717618.191063163790559.173242644717630.766828821
#Sta/Elev= 30
9854.873 219.1699864.712219.52229874.829219.53139884.946219.7893 9905.18219.3498
9915.297219.48249935.737  218.549945.996217.88849956.254 213.1979966.512206.8607
9976.771200.85459987.029200.54749997.288199.7097   10001199.770610007.48 200.176
10017.68202.311710027.89206.436310038.09212.466810038.62212.5501 10048.3213.0467
10058.46213.243710068.56215.091510078.66 218.95210088.76 224.48310098.86227.2571
10108.95225.736610119.05225.914710129.15226.478110139.25226.610610145.13226.5232
#Mann= 3 , 0 , 0
9854.873    0.04       09854.873    0.04       010145.13    0.04       0
#XS Ineff= 2 , 0
       0                               0
Bank Sta=9854.873,10145.13
Exp/Cntr=0.3,0.1

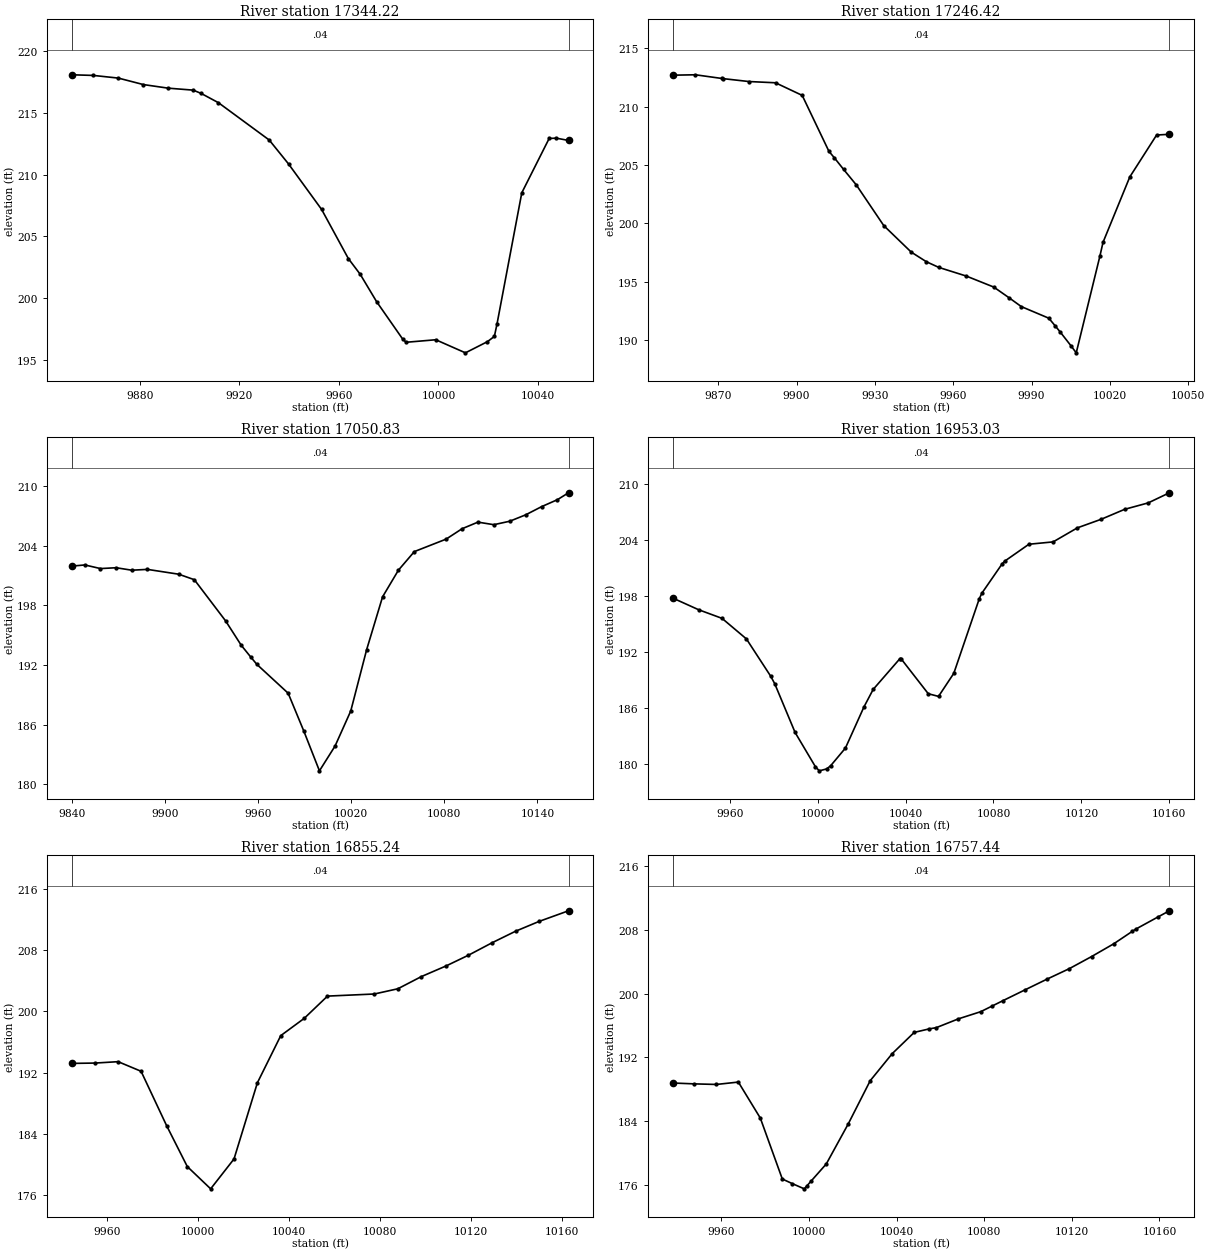
Type RM Length L Ch R = 1 ,17344.22,97.795500,97.795500,97.795500
XS GIS Cut Line= 6
790833.678095043 717555.54741329790781.840251595717551.815224424
790747.405879945717544.742712975790720.537902951717534.263611004
790677.534149319717506.602326363790647.935971349717492.944566101
#Sta/Elev= 25
9852.614218.08849861.315218.03559871.341217.81919881.367217.29579891.393217.0026
9901.419216.84419904.586216.5795 9911.57215.82429931.987212.7993 9939.74210.8632
9953.056207.17149963.789203.19429968.579201.91369975.161199.69799985.717196.6449
9987.047196.40979998.933196.613710010.86195.553210019.71196.4589 10022.5196.8859
10023.54197.870910033.52208.522510044.53212.929710047.41212.951410052.31212.7673
#Mann= 3 , 0 , 0
9852.614    0.04       09852.614    0.04       010052.31    0.04       0
#XS Ineff= 2 , 0
       0                               0
Bank Sta=9852.614,10052.31
Exp/Cntr=0.3,0.1

Type RM Length L Ch R = 1 ,17246.42,195.591000,195.591000,195.591000
XS GIS Cut Line= 6
790883.510834277717479.046526283790822.922168463717466.101295173
 790742.72680378717439.463598281790740.847216934717438.780112162
790736.955297887717437.468827322790700.225955963717429.035811558
#Sta/Elev= 29
 9852.54212.68389861.243 212.7199871.469212.40039871.907212.38799881.695212.1412
 9891.92212.03319902.146210.95419912.372206.16639914.496205.5973 9917.99204.6164
9922.844203.29229933.381199.80089943.919197.52569949.713196.70419954.456196.2192
9964.993 195.477 9975.53194.53279981.437193.60839986.067 192.8629996.605191.8664
    9999 191.223   10001 190.67510005.11189.499610007.11188.899510016.14197.1556
10017.37198.367510027.63203.971410037.89207.558110042.79207.6204
#Mann= 3 , 0 , 0
 9852.54    0.04       0 9852.54    0.04       010042.79    0.04       0
#XS Ineff= 2 , 0
       0                               0
Bank Sta=9852.54,10042.79
Exp/Cntr=0.3,0.1

Type RM Length L Ch R = 1 ,17050.83,97.795500,97.795500,97.795500
XS GIS Cut Line= 5
790883.335832515 717309.40034697790725.537781362717289.536456445
790723.545300186717289.363197212790706.709962009717287.226749225
790568.015710742  717256.3296146
#Sta/Elev= 30
9839.957201.94439848.358202.05979858.437201.69619868.516201.78089878.595201.5319
9888.674201.61399908.832201.12999918.911200.57719939.069196.43199949.147193.9773
9955.255192.79799959.226 192.0559979.384189.15389989.463185.3489 9999.54181.3445
10009.61183.841310019.72187.366510029.97193.542410040.21198.848610050.46201.5395
 10060.7203.404610081.19  204.6610091.44205.703610101.68 206.36910111.93 206.112
10122.17206.459210132.42207.101410142.66207.923210152.91208.628610160.06209.3225
#Mann= 3 , 0 , 0
9839.957    0.04       09839.957    0.04       010160.06    0.04       0
#XS Ineff= 2 , 0
       0                               0
Bank Sta=9839.957,10160.06
Exp/Cntr=0.3,0.1

Type RM Length L Ch R = 1 ,16953.03,97.795500,97.795500,97.795500
XS GIS Cut Line= 6
 790846.14011515717252.828306918790825.897925595717245.748415611
790780.297291724717224.228754433790746.618522563717198.314157937
790716.115920388717180.363908867790645.991555027717150.803842568
#Sta/Elev= 30
 9934.09197.82629945.878196.57159956.534195.64579967.613 193.4439978.693189.4334
9980.505188.63649989.772183.4059    9999179.737910000.78179.294410004.17179.5046
10005.97179.850510012.66181.7364 10021.1186.155210025.27188.0227 10037.5191.3394
10037.89191.336410050.34187.5622   10055 187.27710061.95189.751410073.55197.7581
10074.72198.345610083.86201.464910085.09201.777310096.11203.592710107.14203.8454
10118.17205.353110128.97206.269410139.67207.339410150.37208.026610160.01209.1115
#Mann= 3 , 0 , 0
 9934.09    0.04       0 9934.09    0.04       010160.01    0.04       0
#XS Ineff= 2 , 0
       0                               0
Bank Sta=9934.09,10160.01
Exp/Cntr=0.3,0.1

Type RM Length L Ch R = 1 ,16855.24,97.795400,97.795400,97.795400
XS GIS Cut Line= 6
790855.177427429717140.135891864790813.847874689717134.385942781
790801.255203052  717131.5358497790799.321455444717131.025339965
790729.482635192717114.390779989790642.488589284717091.040259732
#Sta/Elev= 21
9944.361193.20049954.637193.24489964.733193.42599974.829192.17139986.089185.0555
 9995.16179.727610005.44176.817910015.72180.7226   10026190.669510036.28196.8267
10046.56 199.07210056.84201.989510077.43 202.26310087.79202.946910098.14204.5384
10109.02205.930510118.85207.3308 10129.2208.949410139.56210.459710149.91211.7432
10162.87213.1327
#Mann= 3 , 0 , 0
9944.361    0.04       09944.361    0.04       010162.87    0.04       0
#XS Ineff= 2 , 0
       0                               0
Bank Sta=9944.361,10162.87
Exp/Cntr=0.3,0.1

Type RM Length L Ch R = 1 ,16757.44,97.795500,97.795500,97.795500
XS GIS Cut Line= 5
790874.879058877717039.318151846790813.871862376717034.472979677
790811.876181891717034.341604636 790758.15724371717029.523826877
790649.922348666717012.336584772
#Sta/Elev= 30
9937.801188.78739947.711188.67859957.742188.60589967.774188.90469977.805184.3808
9987.837176.73259992.343176.15989997.868175.4968    9999175.8503   10001176.4756
 10007.9178.617510017.94183.653610027.98189.083910038.02192.479710048.06195.1441
10054.93195.586110058.13195.739910068.26196.848310078.38197.741210083.78198.4763
10088.51199.122310098.63200.485410108.76 201.84310118.88203.152510129.01204.6669
10139.13206.270810147.54207.823210149.26208.123910159.38209.648910164.53210.4159
#Mann= 3 , 0 , 0
9937.801    0.04       09937.801    0.04       010164.53    0.04       0
#XS Ineff= 2 , 0
       0                               0
Bank Sta=9937.801,10164.53
Exp/Cntr=0.3,0.1

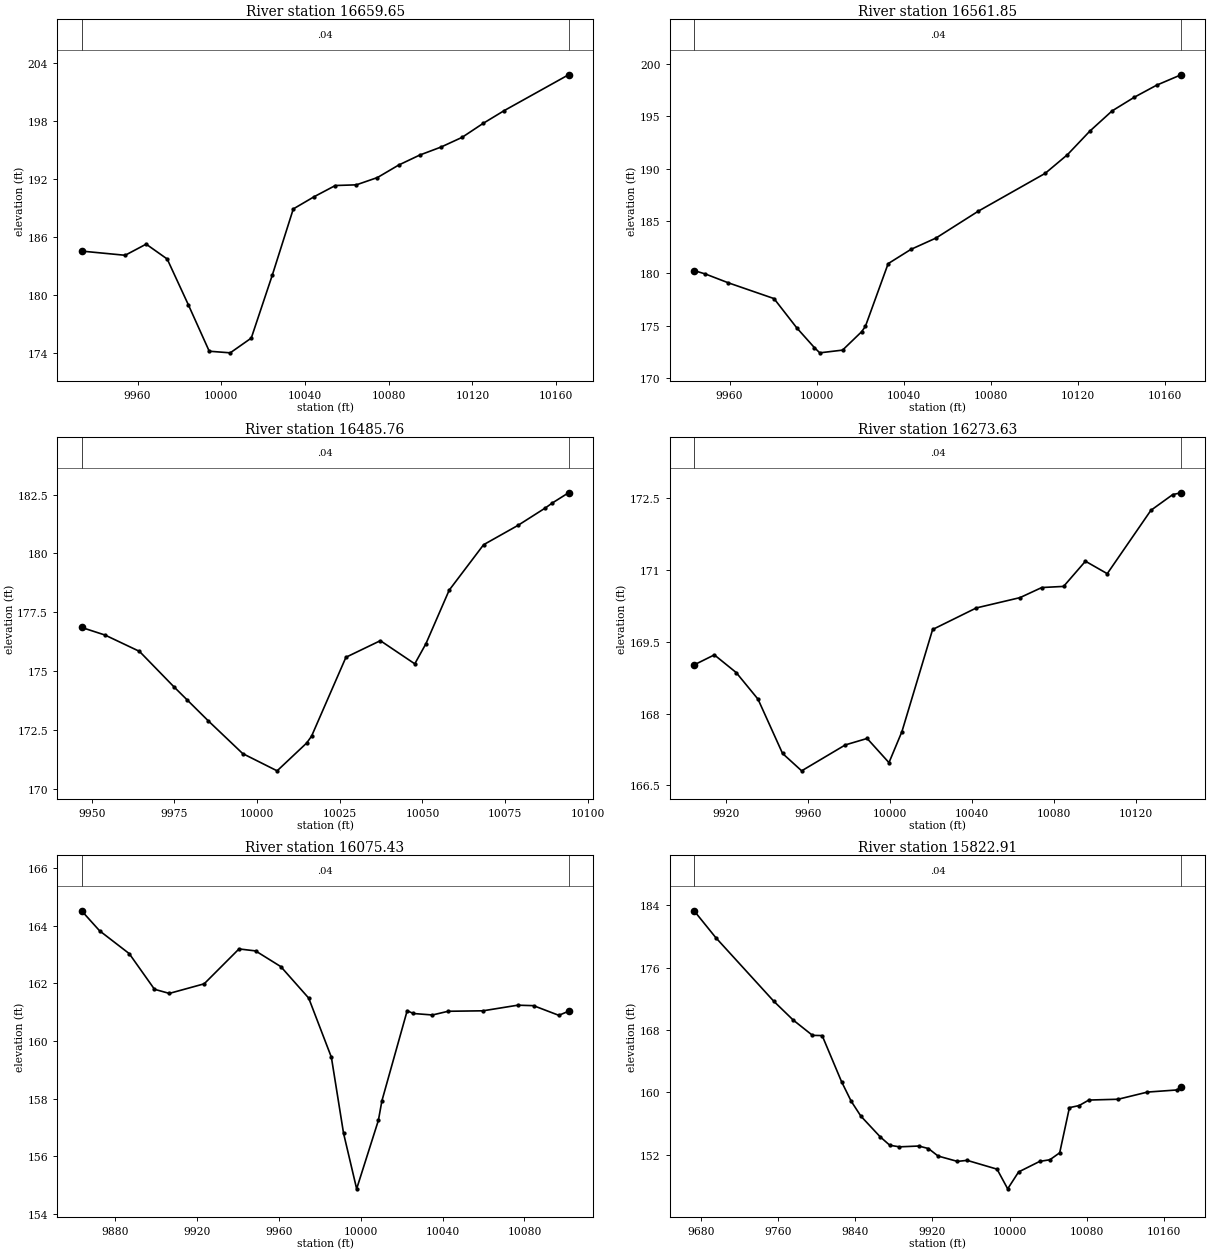
Type RM Length L Ch R = 1 ,16659.65,97.795500,97.795500,97.795500
XS GIS Cut Line= 5
790885.711921998716943.229245478790820.295805904716936.888699927
790818.300125418716936.757324886790753.303233391716930.908153545
 790654.64613444 716916.65437011
#Sta/Elev= 21
9933.277184.56169954.086184.12969964.133185.2783 9974.18183.74519984.227179.0502
9994.274174.230610004.31174.064110014.35175.585310024.39182.076810034.43 188.912
10044.48190.182810054.52191.327510064.56191.396810074.65192.151410084.75193.4354
10094.86194.470310104.96195.290910115.06196.294310125.17197.743610135.27199.0655
10165.94202.7524
#Mann= 3 , 0 , 0
9933.277    0.04       09933.277    0.04       010165.94    0.04       0
#XS Ineff= 2 , 0
       0                               0
Bank Sta=9933.277,10165.94
Exp/Cntr=0.3,0.1

Type RM Length L Ch R = 1 ,16561.85,76.091900,76.091900,76.091900
XS GIS Cut Line= 6
790889.961535288716858.543706066 790888.65268155716858.191501345
790837.356966151716841.535374283790835.470293522716840.871697865
 790784.01537142716824.790676177 790674.02660395716800.348349779
#Sta/Elev= 21
9943.712180.27419948.908179.94719959.422179.1074 9980.45177.60139990.964174.7957
    9999 172.92810001.49172.425310011.97172.684910020.68  174.4310022.45174.9426
10032.92180.9337 10043.4182.295310054.91183.375810074.39185.942310105.12189.5478
10115.36191.330910125.61193.569710135.85195.500410146.14 196.81510156.34197.9572
10167.58 198.951
#Mann= 3 , 0 , 0
9943.712    0.04       09943.712    0.04       010167.58    0.04       0
#XS Ineff= 2 , 0
       0                               0
Bank Sta=9943.712,10167.58
Exp/Cntr=0.3,0.1

Type RM Length L Ch R = 1 ,16485.76,212.132500,212.132500,212.132500
XS GIS Cut Line= 2
790911.813340485716783.850495443790770.320284933716743.051884308
#Sta/Elev= 20
 9946.92176.86069954.011176.53759964.418175.84519974.825174.34439978.864 173.783
9985.233172.8977 9995.64171.508310006.05170.775910014.96171.952610016.46172.2446
10026.86175.594710037.27176.298510047.68175.316110051.05176.169710058.08178.4412
10068.49180.3704 10078.9181.192210087.15181.928910089.31182.144210094.18182.5741
#Mann= 3 , 0 , 0
 9946.92    0.04       0 9946.92    0.04       010094.18    0.04       0
#XS Ineff= 2 , 0
       0                               0
Bank Sta=9946.92,10094.18
Exp/Cntr=0.3,0.1

Type RM Length L Ch R = 1 ,16273.63,198.192900,198.192900,198.192900
XS GIS Cut Line= 2
790994.278618246716599.822717637790771.188340485716518.225495428
#Sta/Elev= 20
9904.602169.01839914.482169.2277 9925.13168.85919935.778168.30279947.754167.1682
9957.074 166.8059978.369167.34679989.017167.48159999.665166.976210005.98167.6237
10020.96169.758310042.26170.208210063.55170.4234 10074.2170.634710084.85170.6583
 10095.5171.184810106.14170.924410127.44172.248210138.09172.576810142.15172.6145
#Mann= 3 , 0 , 0
9904.602    0.04       09904.602    0.04       010142.15    0.04       0
#XS Ineff= 2 , 0
       0                               0
Bank Sta=9904.602,10142.15
Exp/Cntr=0.3,0.1

Type RM Length L Ch R = 1 ,16075.43,252.523400,252.523400,252.523400
XS GIS Cut Line= 2
791100.181396018 716533.85049542  790960.4244516716341.142162106
#Sta/Elev= 24
 9863.51164.51399872.335163.81849886.796163.02849899.149161.79059906.402161.6476
9923.435161.98029940.468163.1906 9948.56163.12189960.913162.57659974.535161.4849
9985.619159.43399991.568156.79679997.972154.8686 10008.6157.244110010.33157.9241
10022.68161.049110025.63 160.95110035.03160.899210042.67 161.02810059.74161.0443
10076.73161.238910084.44161.2225 10096.8160.887310101.56161.0291
#Mann= 3 , 0 , 0
 9863.51    0.04       0 9863.51    0.04       010101.56    0.04       0
#XS Ineff= 2 , 0
       0                               0
Bank Sta=9863.51,10101.56
Exp/Cntr=0.3,0.1

Type RM Length L Ch R = 1 ,15822.91,279.010000,279.010000,279.010000
XS GIS Cut Line= 6
791457.423143625716262.469282657791292.798834443716253.000368804
 791187.15640536716252.247779086791149.554515749 716258.32641238
791098.679029495716281.427975595 790960.64262262716301.648658797
#Sta/Elev= 30
9673.107183.31069695.568179.86399755.667171.6964  9775.7169.29139795.733167.3205
9805.749 167.2929825.782161.38669835.799158.87049845.805156.95929865.811154.2997
9875.814153.21289885.817153.01189905.822153.11529915.823152.79219925.825151.8293
9945.839151.14279955.893151.27599986.864150.1469 9997.89147.620810009.19149.7887
 10031.1 151.14610041.56151.351610051.75152.246710061.82 158.04210071.83158.3073
10081.94159.0159 10112.3159.121910142.67160.041110173.03160.310910177.45160.6538
#Mann= 3 , 0 , 0
9673.107    0.04       09673.107    0.04       010177.45    0.04       0
#XS Ineff= 2 , 0
       0                               0
Bank Sta=9673.107,10177.45
Exp/Cntr=0.3,0.1

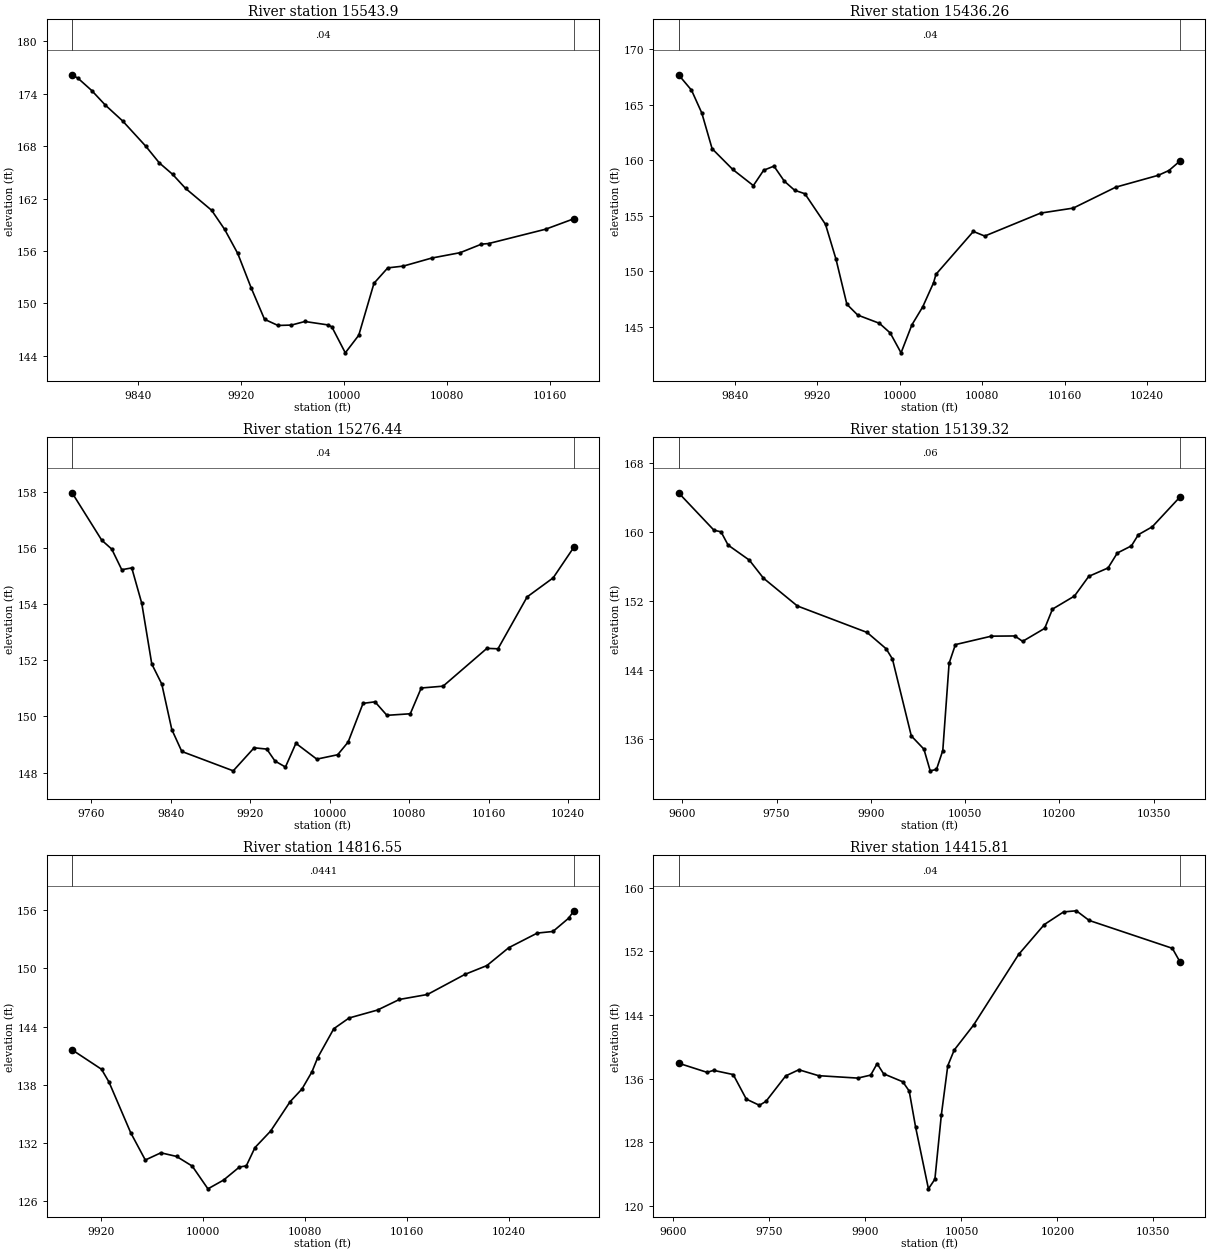
Type RM Length L Ch R = 1 , 15543.9,107.636800,107.636800,107.636800
XS GIS Cut Line= 6
791239.505469859716077.039283797791172.231164306716055.337894902
791111.467275441716045.572269902 791019.23637265716073.784075454
791004.045400441716087.889978215790944.366580993 716214.84310323
#Sta/Elev= 30
9788.858176.14559793.592175.73219804.099174.34739814.607  172.699828.074170.8743
9846.129167.97269856.637166.0677 9866.87164.77289876.998163.15489897.255160.6495
9907.383158.45919917.511155.71729927.853 151.817 9938.31148.18979948.767147.4844
9959.225147.52959969.682147.93839987.508147.54759990.597147.323110001.05144.3546
10011.51146.368510023.32152.307610034.02154.068210046.11 154.27210068.16155.1913
10090.26155.807210106.77156.778410112.38156.851210156.61158.489310178.55159.6841
#Mann= 3 , 0 , 0
9788.858    0.04       09788.858    0.04       010178.55    0.04       0
#XS Ineff= 2 , 0
       0                               0
Bank Sta=9788.858,10178.55
Exp/Cntr=0.3,0.1

Type RM Length L Ch R = 1 ,15436.26,159.821100,159.821100,159.821100
XS GIS Cut Line= 6
791237.570930004715944.401232153791089.133429974715941.797065482
790992.779263347715973.047065482790973.248013377716009.505398825
790944.061561763 716079.39926973790914.654263347716195.703315496
#Sta/Elev= 30
9785.321167.67879797.894166.29649807.895164.24059817.897161.0303  9837.9159.1655
9857.903157.71299867.905159.09179877.906159.46379887.908158.11529897.909157.2954
9907.911156.98019927.914154.22639938.127151.0794 9948.64147.04039959.152146.0698
9980.178145.32959990.691144.4593 10001.2142.672510011.72145.189810022.23146.8081
10032.74148.977610035.08149.736610071.33153.588710082.39153.175310136.58155.2392
10168.27155.689810209.53157.572710250.79158.6394 10261.1159.069610272.14159.9508
#Mann= 3 , 0 , 0
9785.321    0.04       09785.321    0.04       010272.14    0.04       0
#XS Ineff= 2 , 0
       0                               0
Bank Sta=9785.321,10272.14
Exp/Cntr=0.3,0.1

Type RM Length L Ch R = 1 ,15276.44,137.121500,137.121500,137.121500
XS GIS Cut Line= 6
791164.654263347715859.765815496791037.050096661715844.140815496
 790880.80009672715894.922065482790857.362596631715930.078315496
790828.716763318715992.578315496790784.445930004 716083.72414884
#Sta/Elev= 30
9740.696157.97369770.572156.28299780.646155.96529790.721 155.2319800.796155.2946
 9810.87154.03119820.945151.8697 9831.02 151.1539841.094149.53339851.169148.7503
9902.953148.05959923.983148.8811 9936.74148.83469945.013148.40779955.528148.1956
9966.043149.04059987.072148.4766 10008.1148.633610018.62149.085210033.64150.4652
10045.66150.520410057.68150.038710081.21150.094510092.21151.012910114.22151.0783
10158.36152.427110169.48152.410510198.84154.261610225.06154.940410245.88156.0319
#Mann= 3 , 0 , 0
9740.696    0.04       09740.696    0.04       010245.88    0.04       0
#XS Ineff= 2 , 0
       0                               0
Bank Sta=9740.696,10245.88
Exp/Cntr=0.3,0.1

Type RM Length L Ch R = 1 ,15139.32,322.769400,322.769400,322.769400
XS GIS Cut Line= 6
791255.127805336715879.108243435791104.570860224715801.527111513
790942.244471335715779.825722624790824.005840091715771.770544354
790685.082155464715864.147568063790524.575876531715945.296993253
#Sta/Elev= 30
9594.006 164.5689650.397160.21779661.647160.03159672.897158.48939706.645156.7445
9729.144154.64689783.121151.4151  9894.1148.33899924.366146.44679934.408145.2584
9964.477136.31339984.524134.77949994.547132.256410004.57132.424510014.59 134.619
10024.62144.751910034.64 146.92510091.94147.907110129.24147.929810141.67147.3035
 10176.8148.814410189.17151.050210224.18152.570610246.91154.855510277.63 155.834
10292.37157.569210314.83158.400410325.88159.700510347.98160.615710392.64164.1224
#Mann= 3 , 0 , 0
9594.006    0.06       09594.006    0.06       010392.64    0.06       0
#XS Ineff= 2 , 0
       0                               0
Bank Sta=9594.006,10392.64
Exp/Cntr=0.3,0.1

Type RM Length L Ch R = 1 ,14816.55,400.746000,400.746000,400.746000
XS GIS Cut Line= 4
790826.070791364715532.777738556790810.903039306715538.844839349
790774.010678202715559.461158797 790501.65824765715754.773658797
#Sta/Elev= 30
9897.266141.59569920.365139.5884 9926.22138.27189943.276133.03119954.731130.2125
9966.953130.95659979.258 130.5839991.564129.582810003.87127.234610016.17128.1421
10028.48129.478710034.01 129.61610040.79131.497710053.09133.205110068.33136.2315
 10077.7 137.55410085.49 139.32210090.01140.789710102.64143.776910114.62144.8831
10136.96145.705810154.12146.799810176.15147.3136 10205.6149.392410222.76150.2981
10239.92152.146710262.29153.655410274.59153.8213 10286.9 155.19110291.01155.9596
#Mann= 3 , 0 , 0
9897.266  0.0441       09897.266  0.0441       010291.01  0.0441       0
#XS Ineff= 2 , 0
       0                               0
Bank Sta=9897.266,10291.01
Exp/Cntr=0.3,0.1

Type RM Length L Ch R = 1 ,14415.81,241.171800,241.171800,241.171800
XS GIS Cut Line= 6
791038.657356457715248.812325777790780.998241111715306.241608964
790726.151000902715313.673720015790663.240514783715312.295975744
790452.508583955715289.998665935790262.526562815715289.316150856
#Sta/Elev= 30
9607.873137.95429652.479136.80269662.696137.05289693.348136.52469713.783133.4448
9734.304132.6673 9744.57133.16389775.368136.3566  9795.9137.12949826.697136.3855
9888.014136.08139908.197136.45789918.288137.89299928.369136.62249958.379135.6194
9968.392134.45889978.406129.9302 9998.47122.182510008.55123.391410018.62131.4388
10028.69 137.63110038.76 139.60210068.98142.732410139.42 151.59810179.56155.3538
10209.64156.936210229.65157.080510249.66 155.86910379.69152.371410392.17150.5904
#Mann= 3 , 0 , 0
9607.873    0.04       09607.873    0.04       010392.17    0.04       0
#XS Ineff= 2 , 0
       0  9919.8                       0
Bank Sta=9607.873,10392.17
Exp/Cntr=0.3,0.1