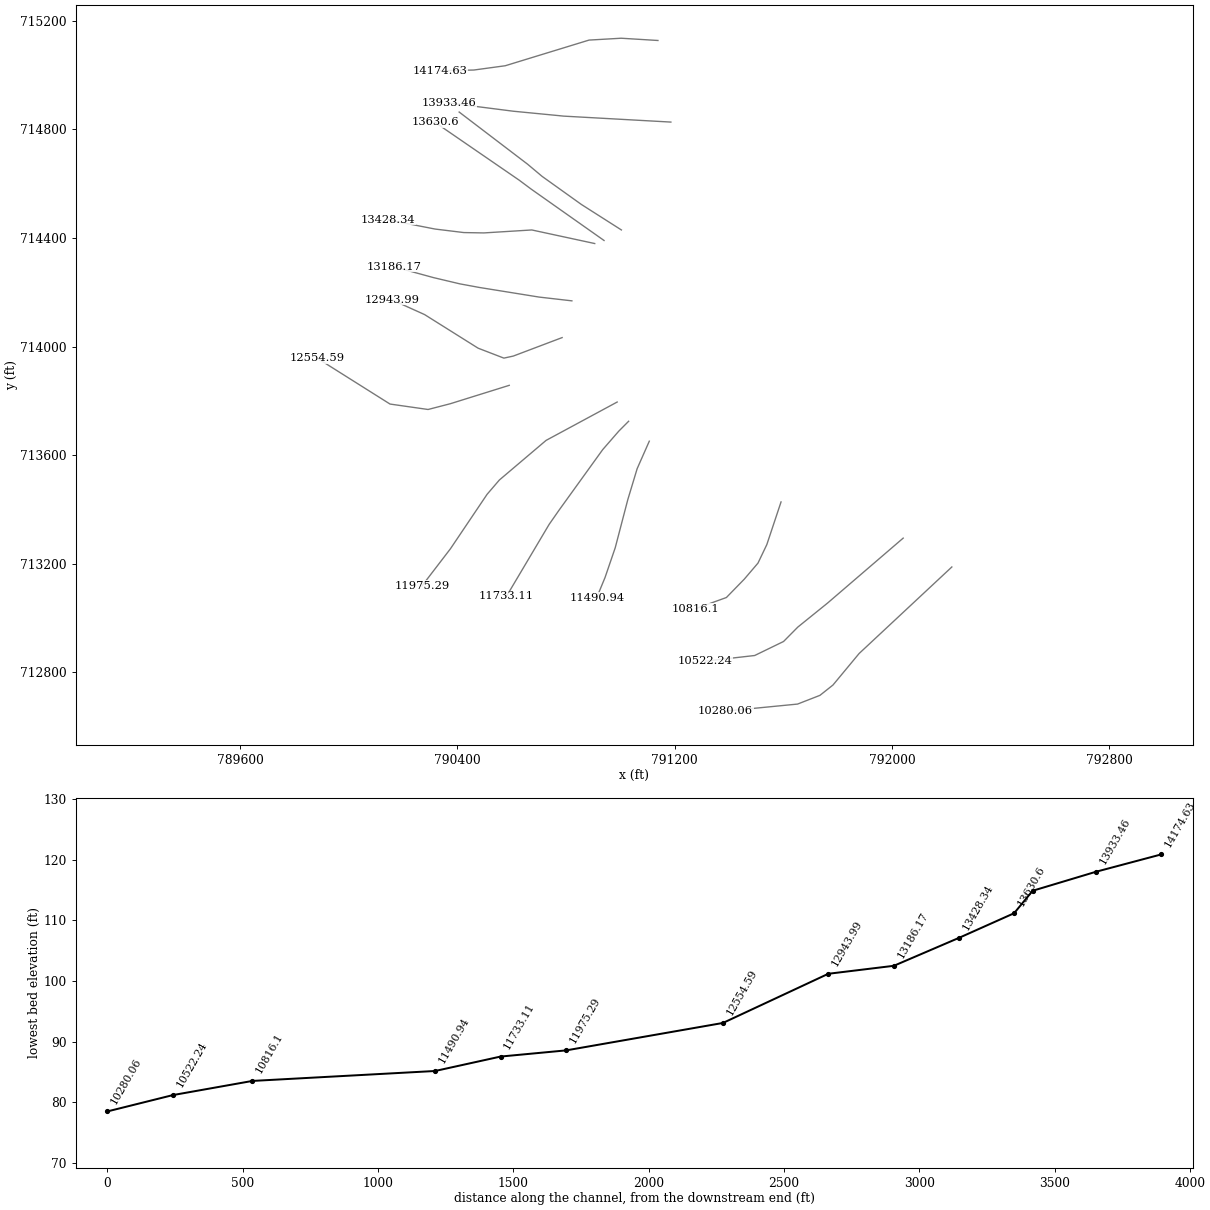
HEC-RAS study 6662_ras.prj: 6662

--- 6662_ras.g01 (geometry) --- (continued)

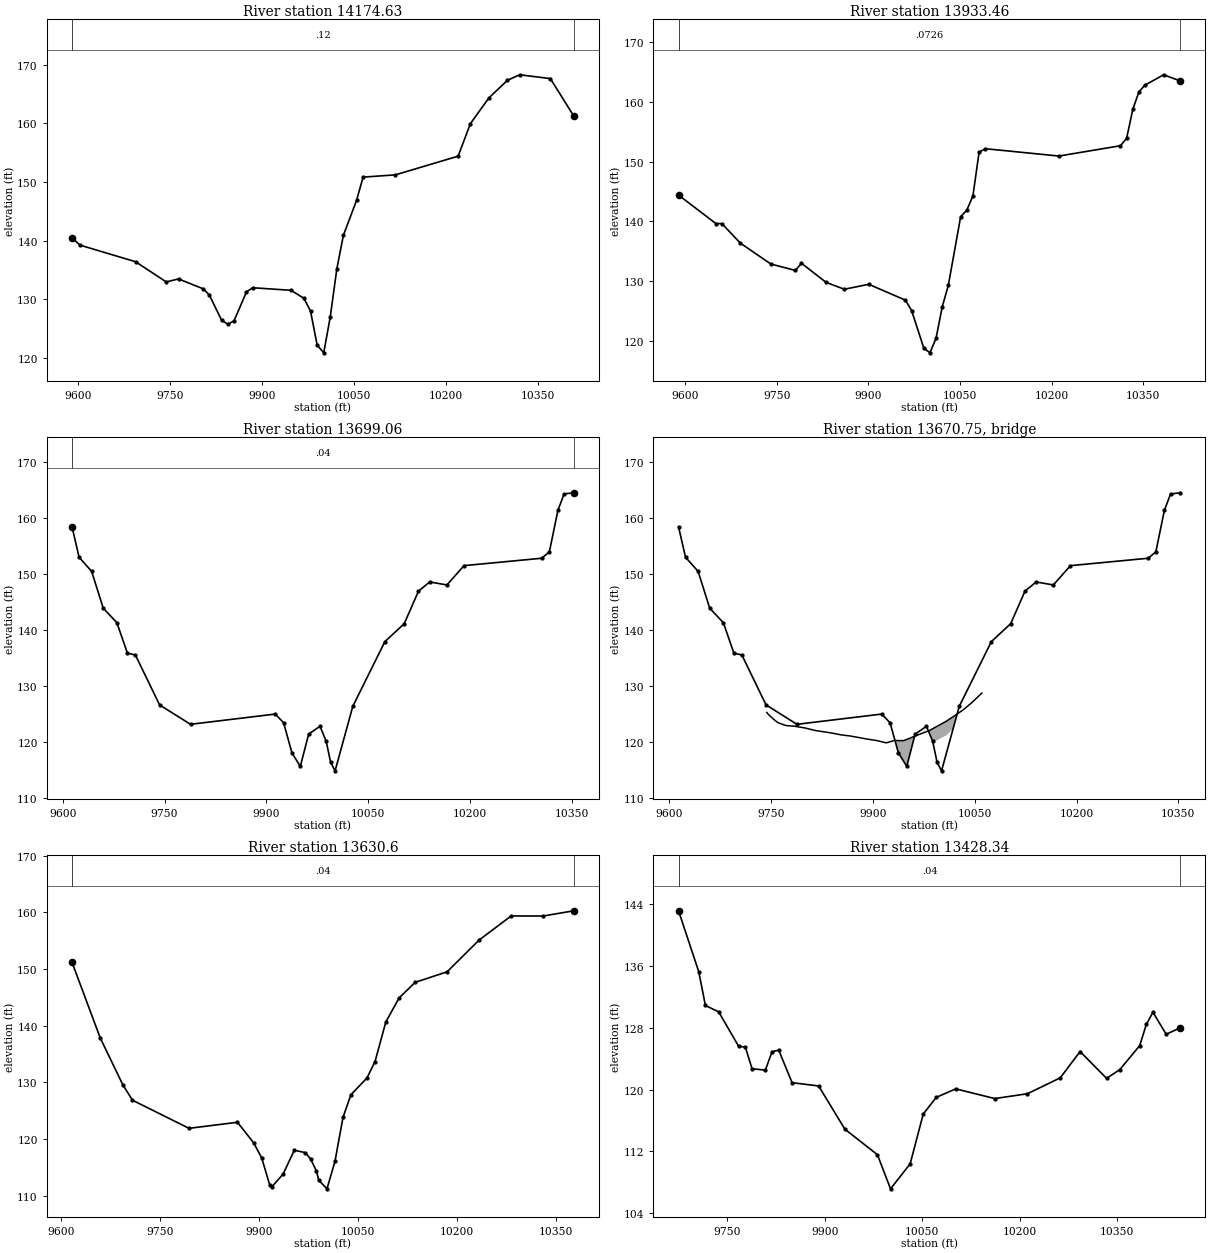
Type RM Length L Ch R = 1 ,14174.63,241.171700,241.171700,241.171700
XS GIS Cut Line= 6
791138.298823502715127.231003349791002.894769558715135.536150496
790884.654915951715128.709784872790575.984268015715034.206926397
790460.210326347715018.422478784790336.659734597715015.874797556
#Sta/Elev= 30
9590.905140.44199604.244139.2471 9694.46136.43119744.488132.99059764.493133.5015
9804.557131.82389814.612130.77969834.723126.47429844.779125.78289854.943126.3455
9875.281131.28799885.484132.00199947.943131.56159969.062130.19179979.797127.9864
9990.531 122.22310001.28120.908710011.97 127.08710022.66135.242210033.35140.9519
10054.73146.868910065.42150.844710118.01151.234710220.34154.415410240.46159.9671
10270.62164.356810300.72167.338910320.74 168.28610370.76167.6383 10409.1161.2352
#Mann= 3 , 0 , 0
9590.905    0.12       09590.905    0.12       0 10409.1    0.12       0
#XS Ineff= 2 , 0
       09928.468                       0
Bank Sta=9590.905,10409.1
Exp/Cntr=0.3,0.1

Type RM Length L Ch R = 1 ,13933.46,234.402800,234.402800,234.402800
XS GIS Cut Line= 6
791186.002759076714826.769494434790791.013758918714848.699003026
790776.880171768714850.107845608790774.894317569714850.345296867
 790606.40201226 714866.66890448 790367.82057245714897.137173972
#Sta/Elev= 30
9589.199  144.419650.296139.65539660.311139.63199690.357136.38429740.434132.8852
9780.496 131.8189790.511133.01689830.573129.83859860.619128.66969900.681129.5033
9960.773126.84739970.789125.1122 9990.84118.822810000.89118.045210010.94120.5302
10020.99125.735110031.03129.373310051.13140.805710061.17141.877510071.22144.2737
10081.27151.565110091.32152.164410212.02150.933310312.83152.661710322.91153.9147
10332.99158.733110343.08161.689310353.16162.8043 10383.4164.5169 10410.8163.4829
#Mann= 3 , 0 , 0
9589.199  0.0726       09589.199  0.0726       0 10410.8  0.0726       0
#XS Ineff= 2 , 0
       0                               0
Bank Sta=9589.199,10410.8
Exp/Cntr=0.3,0.1

Type RM Length L Ch R = 1 ,13699.06,68.463800,68.463800,68.463800
XS GIS Cut Line= 5
791003.705554232714429.517970644790856.570137545714523.267970644
 790711.85000132714626.738485329790658.030556902714671.877374224
790406.294445768   714863.717652
#Sta/Elev= 30
9613.778158.3576  9624.1152.95229642.589150.44129659.673143.88259679.808141.2856
9695.245135.88929707.102135.52869742.675126.64649788.243123.18939913.103125.0141
9925.396123.45869937.689118.07319949.982115.70539962.275 121.4459979.003122.8416
9988.139120.13739994.565116.444810001.19114.900810027.29126.397710074.54137.9179
10103.06141.120510124.03146.904710140.53148.548910165.93148.016710191.07151.4565
10305.51152.7725 10316.8153.901210329.37161.292910338.51 164.23110352.89164.4358
#Mann= 3 , 0 , 0
9613.778    0.04       09613.778    0.04       010352.89    0.04       0
#XS Ineff= 2 , 0
       09981.986                       0
Bank Sta=9613.778,10352.89
Exp/Cntr=0.3,0.1

Type RM Length L Ch R = 3 ,13670.75,,,
BEGIN DESCRIPTION:
END DESCRIPTION:
Bridge Culvert--1,0,-1,-1, 0
Deck Dist Width WeirC Skew NumUp NumDn MinLoCord MaxHiCord MaxSubmerge Is_Ogee
19.231900,30.000000,2.6,0, 53, 53, , , 0.95, 0, 0,0,,
 9743.83 9746.64 9754.37 9759.92 9769.58 9773.19 9784.79 9786.46 9799.74 9799.99
 9813.01 9815.20 9826.28 9830.41 9839.56 9845.62 9852.83 9860.82 9866.10 9876.03
 9879.37 9891.24 9892.65 9905.92 9906.45 9919.19 9921.66 9925.52 9932.19 9937.56
 9944.93 9953.70 9957.67 9969.83 9970.41 9983.15 9983.64 9983.64 9985.97 9995.89
10002.1110008.6310018.2510019.6410019.6410020.0810021.2910033.2410036.2810045.19
10054.5510057.1410060.53
  125.29  124.88  124.03  123.50  123.07  122.95  122.86  122.80  122.55  122.54
  122.15  122.09  121.88  121.81  121.63  121.49  121.32  121.19  121.12  120.90
  120.84  120.56  120.54  120.29  120.28  119.90  119.94  120.09  120.32  120.29
  120.28  120.67  120.88  121.46  121.49  122.08  122.11  122.11  122.26  122.92
  123.33  123.77  124.54  124.65  124.65  124.68  124.79  125.78  126.09  126.99
  128.06  128.37  128.75
 -874.71 -875.12 -875.97 -876.50 -876.93 -877.05 -877.14 -877.20 -877.45 -877.46
 -877.85 -877.91 -878.12 -878.19 -878.37 -878.51 -878.68 -878.81 -878.88 -879.10
 -879.16 -879.44 -879.46 -879.71 -879.72 -880.10 -880.06 -879.91 -879.68 -879.71
 -879.72 -879.33 -879.12 -878.54 -878.51 -877.92 -877.89  119.61  119.76  120.42
  120.83  121.27  122.04  122.15 -875.35 -875.32 -875.21 -874.22 -873.91 -873.01
 -871.94 -871.63 -871.25
 9743.83 9746.64 9754.37 9759.92 9769.58 9773.19 9784.79 9786.46 9799.74 9799.99
 9813.01 9815.20 9826.28 9830.41 9839.56 9845.62 9852.83 9860.82 9866.10 9876.03
 9879.37 9891.24 9892.65 9905.92 9906.45 9919.19 9921.66 9925.52 9932.19 9937.56
 9944.93 9953.70 9957.67 9969.83 9970.41 9981.14 9981.14 9983.15 9985.97 9995.89
10002.1110008.6310017.1410017.1410018.2510020.0810021.2910033.2410036.2810045.19
10054.5510057.1410060.53
  125.29  124.88  124.03  123.50  123.07  122.95  122.86  122.80  122.55  122.54
  122.15  122.09  121.88  121.81  121.63  121.49  121.32  121.19  121.12  120.90
  120.84  120.56  120.54  120.29  120.28  119.90  119.94  120.09  120.32  120.29
  120.28  120.67  120.88  121.46  121.49  121.99  121.99  122.08  122.26  122.92
  123.33  123.77  124.45  124.45  124.54  124.68  124.79  125.78  126.09  126.99
  128.06  128.37  128.75
 -874.71 -875.12 -875.97 -876.50 -876.93 -877.05 -877.14 -877.20 -877.45 -877.46
 -877.85 -877.91 -878.12 -878.19 -878.37 -878.51 -878.68 -878.81 -878.88 -879.10
 -879.16 -879.44 -879.46 -879.71 -879.72 -880.10 -880.06 -879.91 -879.68 -879.71
 -879.72 -879.33 -879.12 -878.54 -878.51 -878.01  119.49  119.58  119.76  120.42
  120.83  121.27  121.95 -875.55 -875.46 -875.32 -875.21 -874.22 -873.91 -873.01
 -871.94 -871.63 -871.25
BR Coef=-1 , 0 , 0 ,, 0 ,,,0.8,0,1,0,
WSPro=,,,, 1 ,,,, 0 ,,,, 0 ,,,,-1 ,-1 ,-1 , 0 , 0 , 0 , 0 , 0
BC Design=,, 0 ,, 0 ,,,,,,

Type RM Length L Ch R = 1 , 13630.6,202.252700,202.252700,202.252700
XS GIS Cut Line= 4
790939.811571171714390.740308323790671.706018252714579.801100774
790627.435184919714612.787211886 790316.67129603714826.328878552
#Sta/Elev= 30
 9616.87151.15299659.467137.8599 9693.67129.58689708.412126.83999794.066121.8751
9867.484122.94479891.956119.32169904.192116.65829916.429111.83099919.249111.5106
9936.601113.78349953.633118.0127 9970.37117.57259978.236116.47969987.107114.3471
9990.707112.7124 10003.1111.191510015.23 116.04510027.36123.789510039.36 127.806
10063.76130.7698 10075.9133.658110092.33140.6663 10112.3144.882210136.56147.6355
 10185.1149.511110233.59155.110210282.16159.3667 10330.7159.3597 10377.2160.2831
#Mann= 3 , 0 , 0
 9616.87    0.04       0 9616.87    0.04       0 10377.2    0.04       0
#XS Ineff= 2 , 0
       09977.314                       0
Bank Sta=9616.87,10377.2
Exp/Cntr=0.3,0.1

Type RM Length L Ch R = 1 ,13428.34,242.175600,242.175600,242.175600
XS GIS Cut Line= 6
790905.487743135714379.528005926790673.838749865714429.507367473
790497.204989934714418.599912353790423.660619408714419.894732167
790317.473751534714432.869905532790143.640011683714466.953392278
#Sta/Elev= 30
9675.112143.18099706.233135.28469716.441130.91019736.856130.08799767.629125.6145
9777.903125.52379788.176122.71619808.724122.53199818.998124.92579829.272125.1212
 9849.82120.90629890.681120.48239931.033114.88459981.162111.570910001.28107.1522
10031.49110.392310051.59116.836310071.63119.006210101.67120.104710161.68118.8488
10211.91119.474210262.43121.535310292.93124.944710333.69121.462910354.08122.6033
10384.65125.705610394.84128.449510405.03130.035710425.41127.178610447.17128.0183
#Mann= 3 , 0 , 0
9675.112    0.04       09675.112    0.04       010447.17    0.04       0
#XS Ineff= 2 , 0
       0                               0
Bank Sta=9675.112,10447.17
Exp/Cntr=0.3,0.1

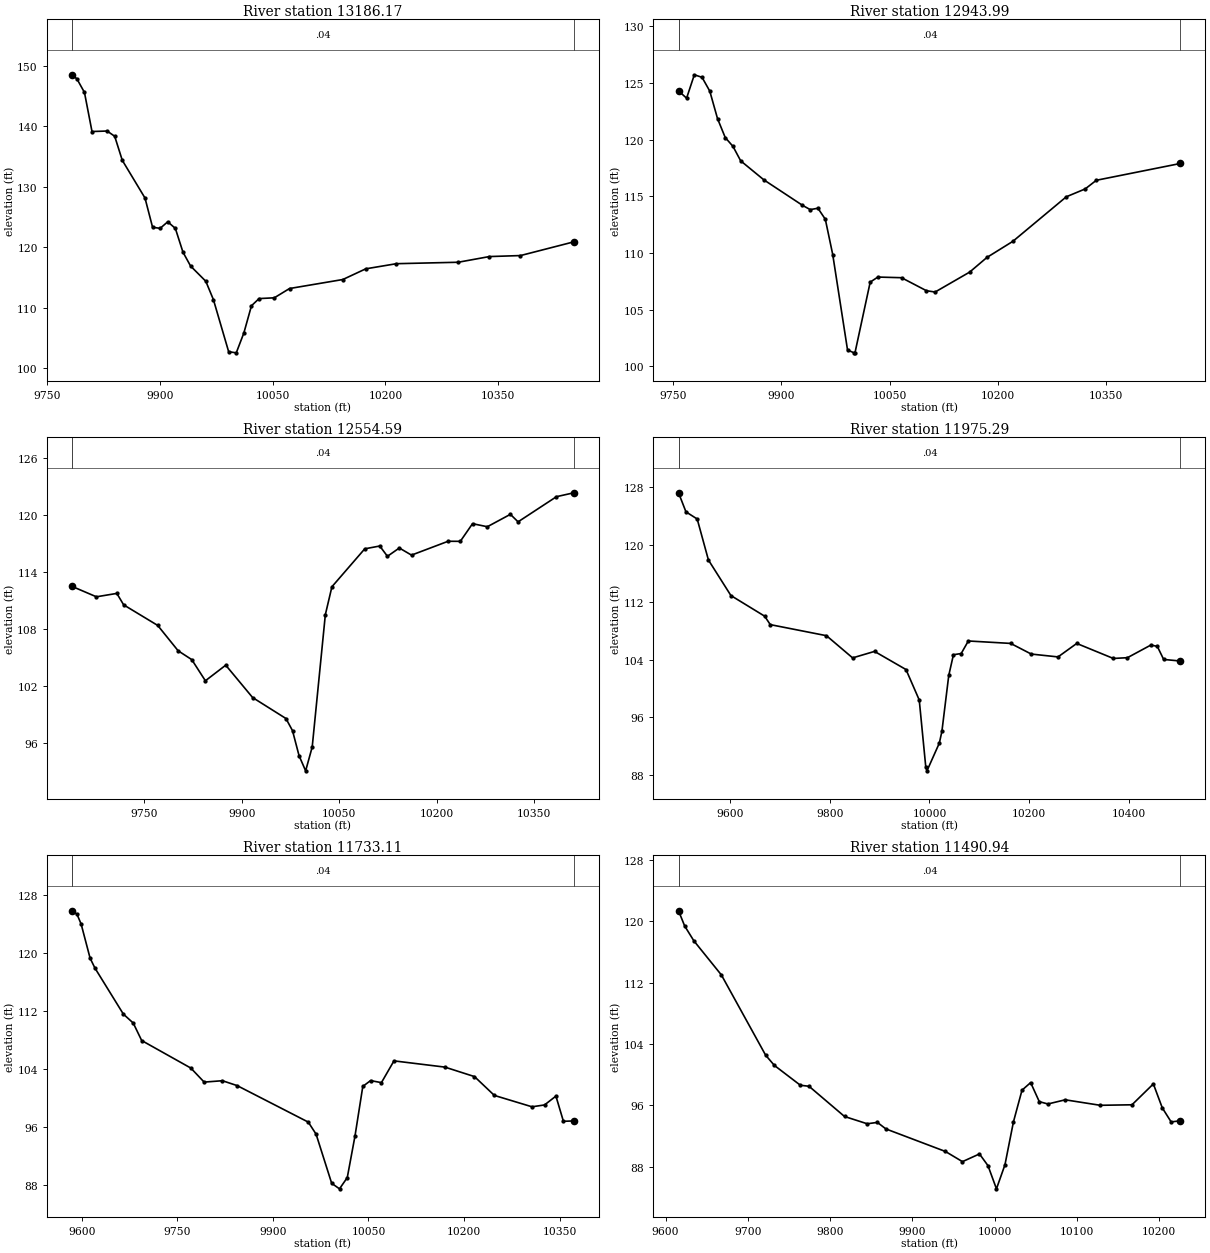
Type RM Length L Ch R = 1 ,13186.17,242.175500,242.175500,242.175500
XS GIS Cut Line= 6
 790821.43656443 714168.47842619790700.580958583 714182.37704208
790480.120556487714217.875450043790409.326065301714230.946181608
790312.203865709714253.937282397790166.485844473714293.767827777
#Sta/Elev= 30
9782.988148.47179789.447147.79269799.483 145.5519809.518 139.0929829.644139.1731
9839.725138.30599849.805134.33529880.047128.09969890.127123.26719900.208123.0872
9910.318124.17289920.452123.07549930.585119.14849940.719116.85879960.986114.3376
 9971.12 111.2969991.387102.696710001.51102.508610011.64105.798210021.76110.2943
10031.89111.476810052.14 111.60510072.39113.138910143.34114.628310173.85116.3949
10214.68117.244810296.89117.482410338.33118.4223 10379.8118.588510450.82120.8561
#Mann= 3 , 0 , 0
9782.988    0.04       09782.988    0.04       010450.82    0.04       0
#XS Ineff= 2 , 0
       0                               0
Bank Sta=9782.988,10450.82
Exp/Cntr=0.3,0.1

Type RM Length L Ch R = 1 ,12943.99,389.405600,389.405600,389.405600
XS GIS Cut Line= 6
790785.441174108714033.156949227 790605.66215387713965.132455096
790570.987800299713957.594552129790476.114867617713994.157694231
790278.861916686714117.989814824 790158.90421378714172.057682568
#Sta/Elev= 30
9758.063 124.3119769.226123.67199779.918125.7359 9790.61125.51059801.302124.2935
9811.994121.87069822.686120.19469833.378119.4176 9844.07118.13939876.145116.4605
9929.605114.21159940.297113.83349950.959113.95619961.192112.98179971.426109.8717
9991.936101.4387   10001101.191210002.26101.203610023.28107.431910033.88107.8805
10066.62107.823310101.12106.675210113.08 106.55810160.92108.318210184.84109.6127
10220.73111.0342 10294.7114.967210320.82115.660210336.22116.423210452.45117.9062
#Mann= 3 , 0 , 0
9758.063    0.04       09758.063    0.04       010452.45    0.04       0
#XS Ineff= 2 , 0
       0                10044.35       0
Bank Sta=9758.063,10452.45
Exp/Cntr=0.3,0.1

Type RM Length L Ch R = 1 ,12554.59,579.296600,579.296600,579.296600
XS GIS Cut Line= 5
790590.731710047713857.363572225790373.717821181713789.655238897
790291.820118159713768.421264529790151.703687161713788.447460592
789882.398376703713958.058016673
#Sta/Elev= 30
9639.177112.49979676.607111.40439708.033111.76249718.509110.55699770.886 108.389
9802.312105.71829823.263104.78669844.214102.55719875.514104.20139916.836100.7913
9968.104 98.58279978.20697.302049988.30894.658559998.40993.0689710008.5195.58353
10028.71109.523610038.82112.462510089.32116.458910112.39 116.75510124.21115.6718
10142.48116.546210161.24115.796410217.54117.2556 10236.3117.248110255.07119.1088
10277.85118.7862 10313.3120.093510325.12119.301610384.21121.954110410.92122.3638
#Mann= 3 , 0 , 0
9639.177    0.04       09639.177    0.04       010410.92    0.04       0
#XS Ineff= 2 , 0
       0                               0
Bank Sta=9639.177,10410.92
Exp/Cntr=0.3,0.1

Type RM Length L Ch R = 1 ,11975.29,242.175600,242.175600,242.175600
XS GIS Cut Line= 6
790988.191570899713795.881845022790726.367683307713654.597371737
790554.382675506713508.740249074790509.180036999713456.104348751
790374.250762158713255.602261125790269.382351316713118.818771178
#Sta/Elev= 30
9496.599127.21719511.479124.56479534.038 123.5719556.598117.86289601.718112.9212
9669.397110.05299680.677108.87839793.426107.33839845.886 104.2519889.853105.1531
9952.984102.63019979.56298.394889992.64889.092589995.06888.54059 10019.992.40325
10025.0494.0349310038.79101.812210048.15104.688110063.76104.860310078.04106.6032
10163.01106.264110204.31104.783410258.04104.385910295.59106.2595   10369104.1733
10397.33104.279510444.46106.042610457.23105.854410469.99104.034210503.42103.8167
#Mann= 3 , 0 , 0
9496.599    0.04       09496.599    0.04       010503.42    0.04       0
#XS Ineff= 2 , 0
       0                               0
Bank Sta=9496.599,10503.42
Exp/Cntr=0.3,0.1

Type RM Length L Ch R = 1 ,11733.11,242.175500,242.175500,242.175500
XS GIS Cut Line= 6
791030.363543469713725.059152693790994.146316167713688.705669524
790934.907018536713620.652034765790774.326602817713397.925574727
 790737.66094542713345.329384622790580.865858119713081.090899989
#Sta/Elev= 30
9584.846125.78419592.446125.33279599.046 123.9679613.161119.25659620.783117.8929
9665.323111.56919680.849110.33419694.107107.92829771.245104.13939792.142102.2078
9820.843102.39879844.007101.72279955.55496.703149967.80195.049259992.29488.28035
10004.5787.5201910016.7689.0653610028.95 94.826410041.14101.615110053.33102.4175
10070.36102.134710090.05105.129710169.97104.2714 10216.4102.967110247.59100.3763
10306.6798.8103210326.3699.0645910344.23100.2811   1035696.8132610372.3896.86787
#Mann= 3 , 0 , 0
9584.846    0.04       09584.846    0.04       010372.38    0.04       0
#XS Ineff= 2 , 0
       0                               0
Bank Sta=9584.846,10372.38
Exp/Cntr=0.3,0.1

Type RM Length L Ch R = 1 ,11490.94,674.834500,674.834500,674.834500
XS GIS Cut Line= 6
791106.457942851713651.682410411791061.792044164713550.607927231
791027.458819965713436.969131648 790981.03674935713259.377880302
790943.600088517713150.036938505790912.523731448713074.760030162
#Sta/Elev= 30
9615.769121.36319623.228119.3812 9634.39117.45029667.876112.99889721.654102.5482
9732.278101.21549763.86598.631469774.38598.498979817.52694.56333 9845.1193.61193
9857.48693.792629867.82692.940939940.20490.002689960.88388.678969981.56389.68214
9991.90288.1582310002.2185.1354810012.54 88.269410022.8793.8670210033.2797.98938
10043.7798.9772310054.2796.4951610064.7796.1912910085.7896.7353510128.3496.01989
10166.9496.0857510192.9498.8064910203.7595.6909410214.5693.8529210225.7194.00431
#Mann= 3 , 0 , 0
9615.769    0.04       09615.769    0.04       010225.71    0.04       0
#XS Ineff= 2 , 0
       0                               0
Bank Sta=9615.769,10225.71
Exp/Cntr=0.3,0.1

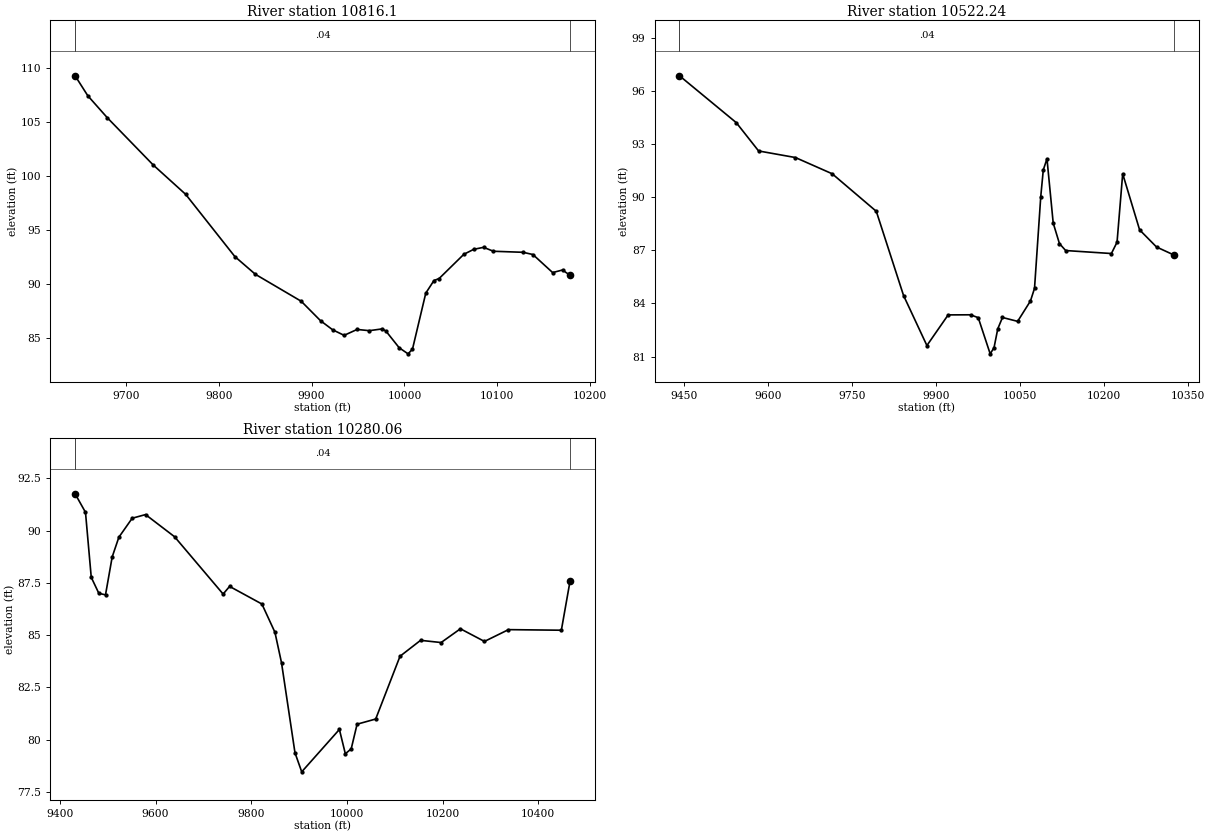
Type RM Length L Ch R = 1 , 10816.1,293.867700,293.867700,293.867700
XS GIS Cut Line= 6
791591.595060873713428.009180196 791539.14027484713270.644822099
791506.674997121713202.762877762791456.327774853713143.735100001
791390.355552644713076.026766658 791277.32717382713035.173135758
#Sta/Elev= 30
9645.123109.31899658.836107.46129679.918105.41389729.224101.04119764.24598.31075
9817.25792.532219839.42790.881029888.82788.377939909.59286.573479922.73685.72442
9935.05685.213439949.02385.760029962.166 85.64759976.02585.811029980.06185.61314
 9994.3984.0590510003.9583.4953510008.7283.9299210023.0589.1345910031.8790.30489
10037.38  90.48610064.0692.7387210074.6993.2008510085.3293.3864910095.9693.02163
10127.8692.9255510138.4992.7197710159.7691.0422510170.3991.2811710178.5590.78504
#Mann= 3 , 0 , 0
9645.123    0.04       09645.123    0.04       010178.55    0.04       0
#XS Ineff= 2 , 0
       0                10172.99       0
Bank Sta=9645.123,10178.55
Exp/Cntr=0.3,0.1

Type RM Length L Ch R = 1 ,10522.24,242.175600,242.175600,242.175600
XS GIS Cut Line= 6
792041.375129351713294.757770442791763.212201449713055.847898985
791653.464273195712967.210988749791600.865579519712914.092907158
  791494.5222193712862.485100001791313.222310736712841.765110445
#Sta/Elev= 30
9442.22496.853039543.58194.207339583.39392.610039649.12292.238049714.72391.32185
9793.44489.20258 9842.0984.448849883.73681.627349921.66883.356759961.61283.36231
9975.35383.199499996.66181.1586710003.5381.5065110010.1982.5695910018.5883.21095
10045.6282.9921310068.5384.1430210075.7884.8564810086.8990.0305810091.4391.54016
10098.0192.1691910109.1288.5395110120.2487.3830210131.3586.9891710212.9786.82071
10223.0487.46093 10233.191.32165 10263.388.1561410293.4987.1888510325.4886.72365
#Mann= 3 , 0 , 0
9442.224    0.04       09442.224    0.04       010325.48    0.04       0
#XS Ineff= 2 , 0
       0                10210.72       0
Bank Sta=9442.224,10325.48
Exp/Cntr=0.3,0.1

Type RM Length L Ch R = 1 ,10280.06,273.525600,273.525600,273.525600
XS GIS Cut Line= 6
792220.564048431713188.527749703791879.029661059712869.772987321
791782.853454739712753.814835846791734.772465557712715.734725192
791652.508330435712683.665655553791386.883330435712657.623988897
#Sta/Elev= 30
9431.87791.763519453.58790.876649465.62587.766789481.48487.000649495.43386.92801
9509.38288.740149523.33189.683889551.22890.593649579.12590.76831  9639.889.70752
9741.31186.966119754.81787.331999822.34786.489259849.57285.138699863.34383.67954
9891.50579.37136 9905.5978.459799984.34880.487729996.76479.3250510009.0479.55853
10021.33 80.739310060.2380.9867210111.0783.9897810154.0484.7517810196.9884.64604
10237.3485.3041310287.5884.6991810337.8285.2635610448.3485.2353110466.5587.59376
#Mann= 3 , 0 , 0
9431.877    0.04       09431.877    0.04       010466.55    0.04       0
#XS Ineff= 2 , 0
       0                10309.79       0
Bank Sta=9431.877,10466.55
Exp/Cntr=0.3,0.1