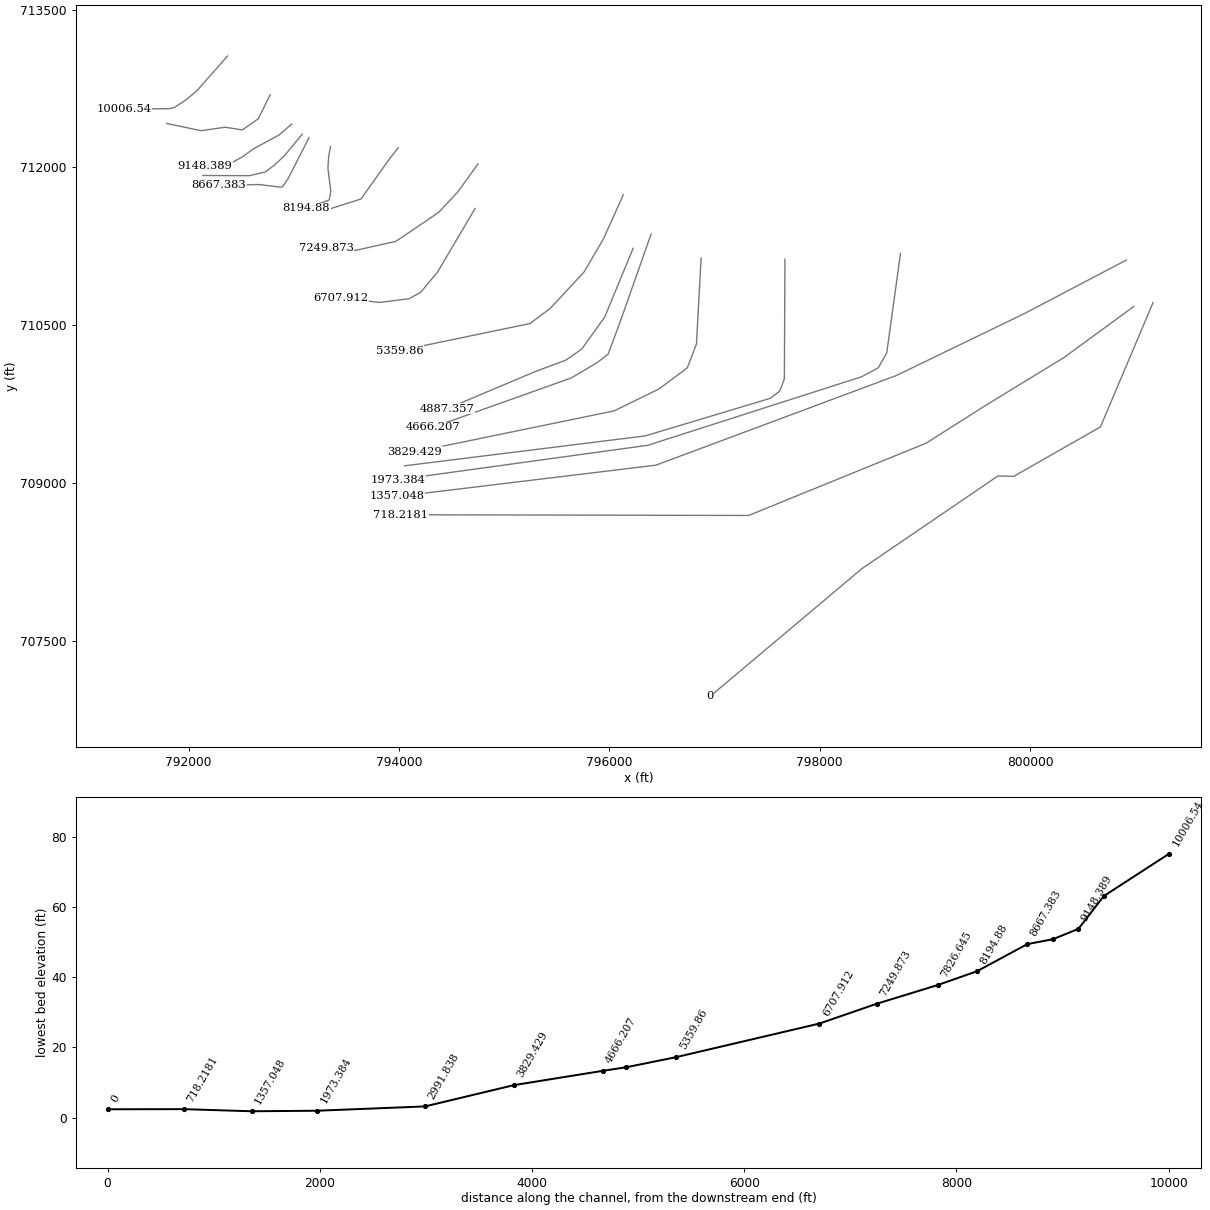
HEC-RAS study 6662_ras.prj: 6662

--- 6662_ras.g01 (geometry) --- (continued)

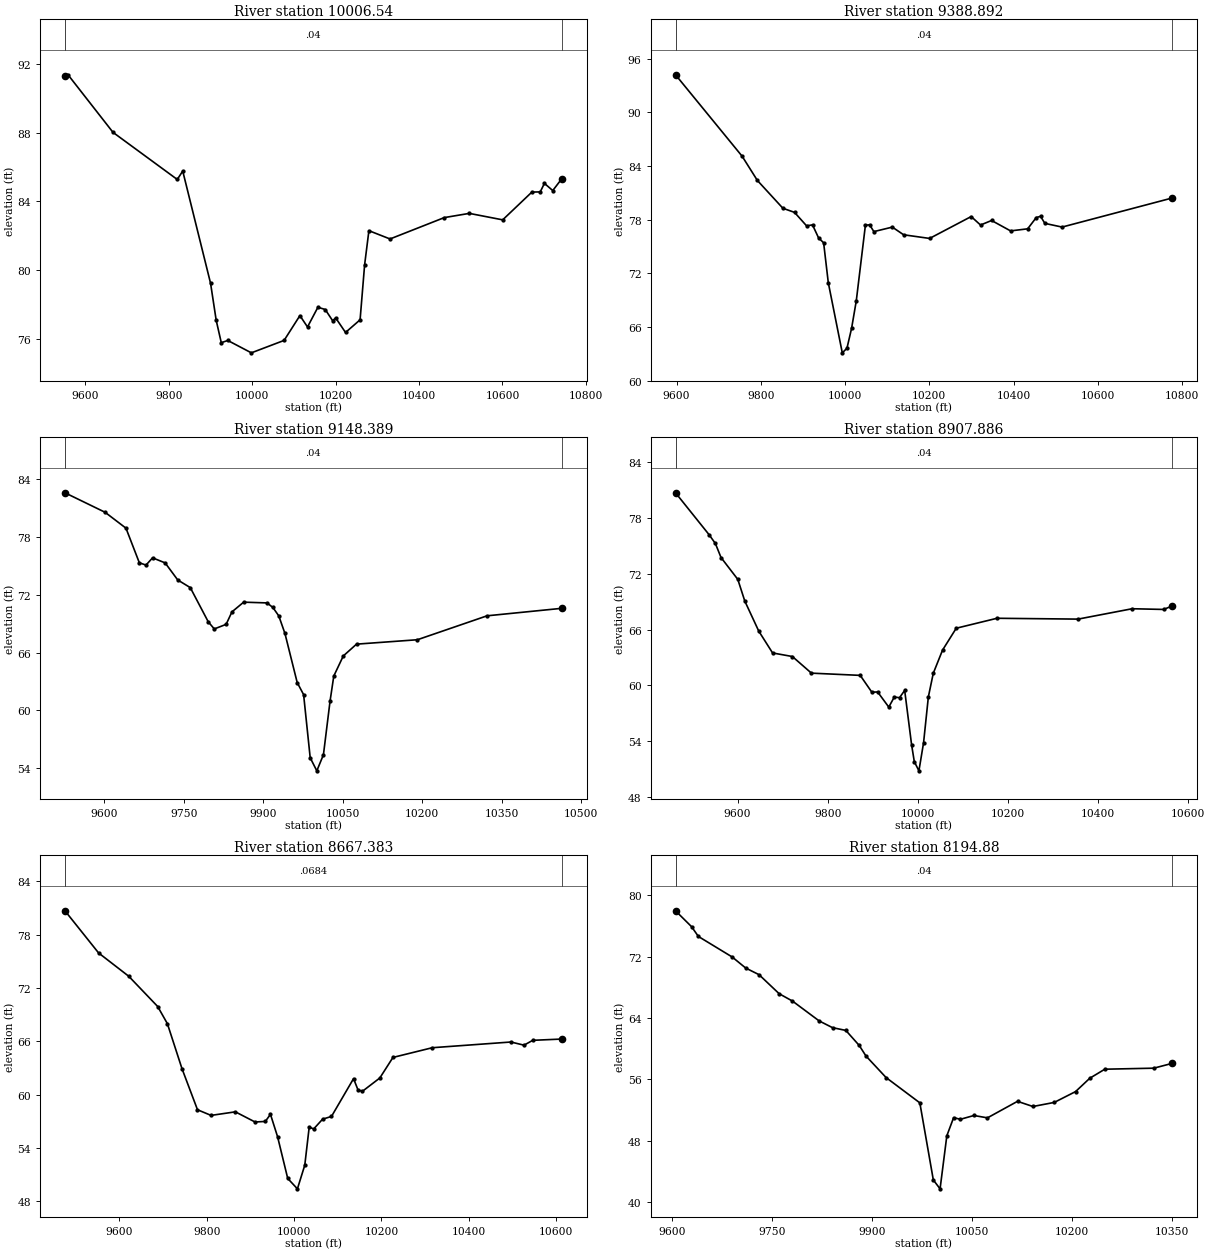
Type RM Length L Ch R = 1 ,10006.54,617.643300,617.643300,617.643300
XS GIS Cut Line= 6
792369.783309944713059.761928022792076.875115712712727.447781055
791970.574576356712639.177266848 791860.87504909712567.990575085
791820.911108226712558.665655553791383.430188647712553.558874396
#Sta/Elev= 30
9551.44391.287739558.81191.361199666.64588.013639820.63285.275299833.77985.76279
9900.47279.240739913.98477.086439926.15775.785859941.76175.91521 9998.2875.19616
10076.72 75.918810114.6177.3605110132.83 76.700510157.7577.8458610175.33 77.7154
10192.9177.0690310200.4177.2243210223.9776.3803410258.8777.1164110269.7280.31267
10279.99  82.29810330.64 81.816410460.6583.0583910520.6583.3031110600.6682.92735
10670.6684.5424910690.6684.5523810700.66 85.048210720.6684.6302610742.2485.31492
#Mann= 3 , 0 , 0
9551.443    0.04       09551.443    0.04       010742.24    0.04       0
#XS Ineff= 2 , 0
       0                10512.02       0
Bank Sta=9551.443,10742.24
Exp/Cntr=0.3,0.1

Type RM Length L Ch R = 1 ,9388.892,240.503200,240.503200,240.503200
XS GIS Cut Line= 6
792775.585919256712691.249288197792661.006045411712461.619704104
792509.617156522712356.064148549792347.117156522712381.758592993
792117.070860225712348.749333734791788.945860225712418.193778178
#Sta/Elev= 30
9597.60494.21131 9755.6985.10334    979282.386049852.51679.279089880.238 78.8148
9908.67477.315069922.89377.415879937.111 75.97529949.24175.412259960.31570.95097
9993.53863.1033810004.6163.6151910015.6965.8658410026.7668.9218810048.4277.38042
10058.4277.4263510068.4976.6666210112.3177.1691710139.1676.3113210200.8175.90284
10299.5378.35069 10321.777.4020910347.9677.9095410393.06 76.7455 10433.676.97795
10453.9778.2365710464.1978.3775210474.4277.58685 10515.377.1733810777.0380.43022
#Mann= 3 , 0 , 0
9597.604    0.04       09597.604    0.04       010777.03    0.04       0
#XS Ineff= 2 , 0
       0                               0
Bank Sta=9597.604,10777.03
Exp/Cntr=0.3,0.1

Type RM Length L Ch R = 1 ,9148.389,240.503200,240.503200,240.503200
XS GIS Cut Line= 6
 792980.37403236712412.957923583792858.260857761712307.425280821
792611.077825313712173.620013134792519.486282195712105.164800945
792422.350633681712051.330586106792155.366406409 712013.91878357
#Sta/Elev= 30
9525.48582.553759601.35180.530869640.71178.885659665.94875.300059678.56775.06255
9690.94575.814039714.70875.287159738.47173.518969762.15672.726869796.15269.17653
9807.48468.447249829.79968.920289840.84170.213649862.92571.220029907.09471.14199
9918.13670.668449929.27269.794659940.85467.981959964.01762.891579976.12661.63892
9988.57655.0949210001.0753.7425310013.5755.4118310026.0660.9693910033.12 63.5664
10051.0465.6458410076.0266.8696310190.93 67.326110322.5669.8060910463.5670.58161
#Mann= 3 , 0 , 0
9525.485    0.04       09525.485    0.04       010463.56    0.04       0
#XS Ineff= 2 , 0
       0                10198.92       0
Bank Sta=9525.485,10463.56
Exp/Cntr=0.3,0.1

Type RM Length L Ch R = 1 ,8907.886,240.503200,240.503200,240.503200
XS GIS Cut Line= 6
793079.193536875712315.965633603792911.021169581712111.266377957
792815.026855653712021.018622174792727.027939046711956.260005543
792580.336744756711921.122252777792135.879001677711922.793146556
#Sta/Elev= 30
9462.18280.712249536.435 76.21959550.64375.259579563.20373.747889600.40871.40036
9615.92869.06968 9646.9765.831569677.61663.486299721.53363.102619763.83461.31405
9872.08161.074619897.88359.266859910.78359.290999935.49257.662729947.66458.73848
9959.30358.678039970.77959.453129986.09653.617179992.12151.7964410002.3850.80743
10012.7153.8382210023.3358.7637910034.2261.2966410054.85 63.7956 10085.2 66.1447
10175.6167.2153610355.6167.1257110475.6168.2414310545.6268.1648110564.7468.54996
#Mann= 3 , 0 , 0
9462.182    0.04       09462.182    0.04       010564.74    0.04       0
#XS Ineff= 2 , 0
       09892.221        10146.41       0
Bank Sta=9462.182,10564.74
Exp/Cntr=0.3,0.1

Type RM Length L Ch R = 1 ,8667.383,472.503300,472.503300,472.503300
XS GIS Cut Line= 6
793144.033954542712282.669202905792945.532582489711893.643561481
792891.462968485711814.792111349792870.194962382711811.891928688
792667.286976248711836.848525926792288.619479604711828.291068363
#Sta/Elev= 30
9475.32480.69192 9552.4475.944979621.40173.327039687.678 69.92349709.89967.99074
9743.23162.945789778.82458.309439809.895 57.67469865.53958.075749910.62756.93219
9934.12456.995749945.90757.794599962.16555.28111 9985.4350.5834210007.6149.41366
10024.4852.0756110034.6356.3621510044.8456.1508210065.24 57.249510085.6557.55904
10136.1461.8102310146.1760.56163 10156.260.3759710196.3161.88291 10226.464.19626
10316.4465.2876210496.4965.93037 10526.565.57498 10546.566.11994 10612.966.26335
#Mann= 3 , 0 , 0
9475.324  0.0684       09475.324  0.0684       0 10612.9  0.0684       0
#XS Ineff= 2 , 0
       09887.145        10204.59       0
Bank Sta=9475.324,10612.9
Exp/Cntr=0.3,0.1

Type RM Length L Ch R = 1 , 8194.88,368.234800,368.234800,368.234800
XS GIS Cut Line= 6
793348.762497146712198.490438844793331.103796824712106.774970718
  793323.9227525  711993.4155158793350.884978963711773.818498966
793336.666316569711690.537762046793118.889193882711609.788941278
#Sta/Elev= 30
9605.71477.981669629.82675.905819640.04774.631369690.79771.951549710.98370.51688
9731.08969.64409  9761.267.165389781.20966.20467 9821.2363.617349841.24662.73863
9861.272 62.3775 9881.3860.412569891.43359.043769921.65956.22751 9972.27 52.9316
9992.51542.8713410002.6441.7162910012.7748.6347210022.9450.9998310033.1250.78663
10053.41 51.2816 10073.750.97449 10118.853.1288910141.91 52.455910173.9152.98673
 10205.954.3989210227.2356.1403510249.7957.3187910323.2257.4530810351.0758.08462
#Mann= 3 , 0 , 0
9605.714    0.04       09605.714    0.04       010351.07    0.04       0
#XS Ineff= 2 , 0
       0                               0
Bank Sta=9605.714,10351.07
Exp/Cntr=0.3,0.1

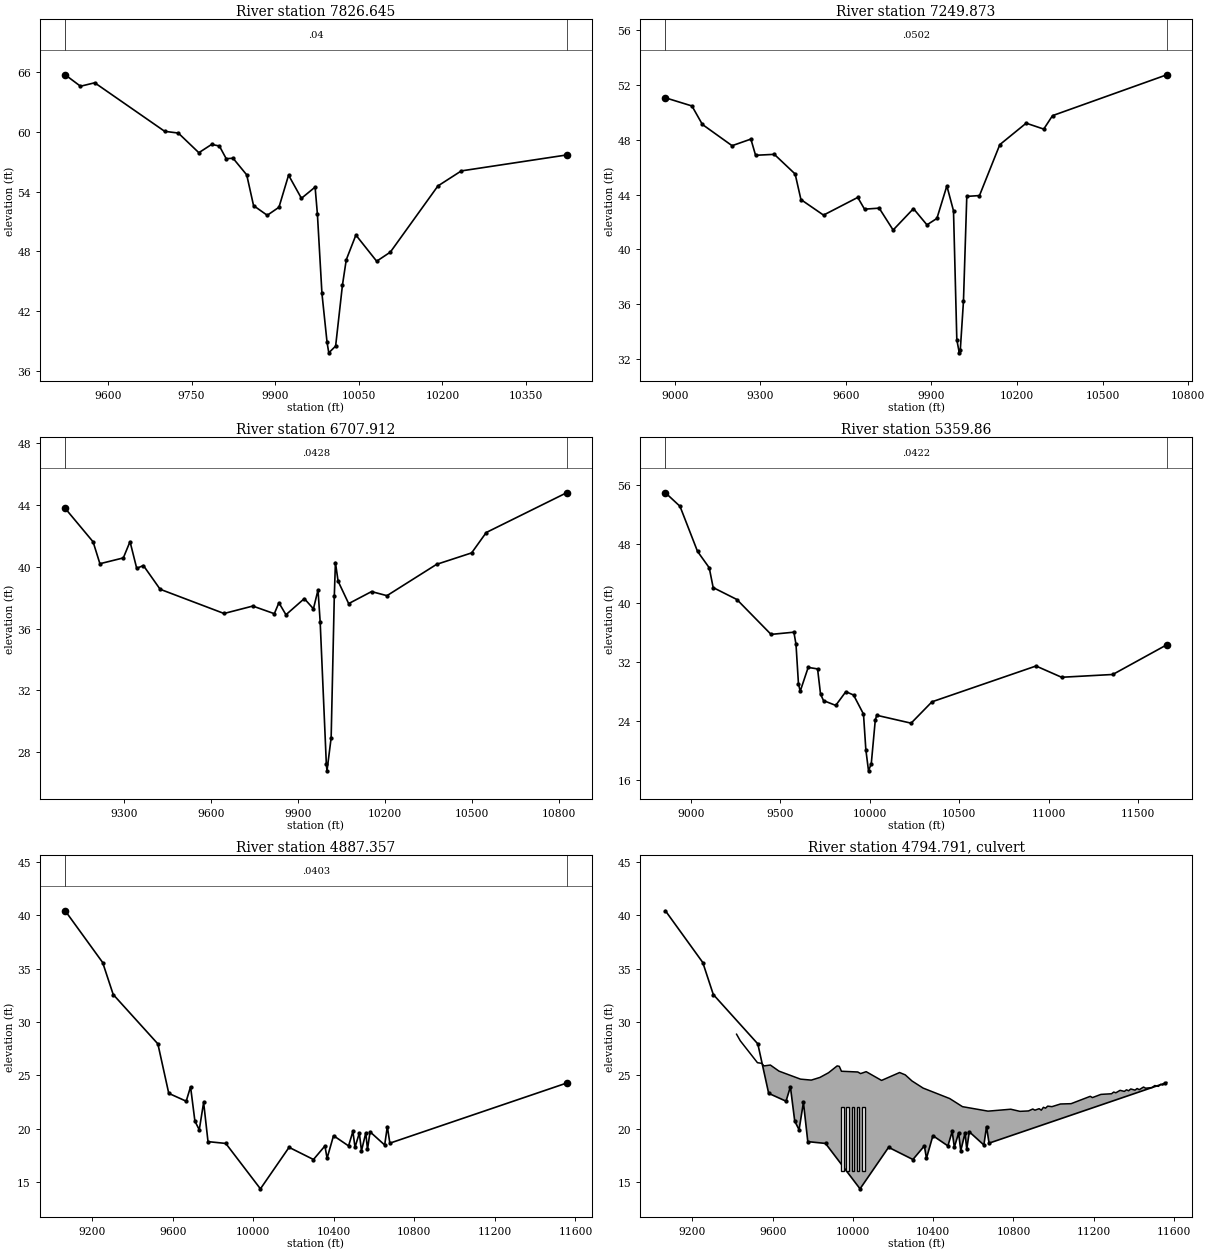
Type RM Length L Ch R = 1 ,7826.645,576.771700,576.771700,576.771700
XS GIS Cut Line= 4
793992.535944521712186.512681633793915.859612912712090.013302088
793638.081835121711699.388302088793355.095723987711609.110524327
#Sta/Elev= 30
9523.13265.753469550.60964.600999576.15464.94891 9701.6260.069559726.16159.89268
9762.97357.918649785.91358.751679799.78558.592369812.05557.317469824.32657.36285
9848.86755.690559861.13852.598389885.67951.626379906.70252.433759923.95855.66033
9947.03253.332559971.57354.462089975.72551.717239983.84443.76554 9992.98 38.8624
9996.11537.7963910008.3938.4765910020.6644.6256710027.4947.1578510044.7549.63841
10082.0147.0083310106.5547.9216110191.9254.5758410233.9156.0884410422.7457.69036
#Mann= 3 , 0 , 0
9523.132    0.04       09523.132    0.04       010422.74    0.04       0
#XS Ineff= 2 , 0
       0                10049.43       0
Bank Sta=9523.132,10422.74
Exp/Cntr=0.3,0.1

Type RM Length L Ch R = 1 ,7249.873,541.961400,541.961400,541.961400
XS GIS Cut Line= 6
794750.143976377 712031.35362996794558.659587106711766.997597668
794377.399797702711572.489716465793969.878371229711296.433813367
793589.270483226711211.371095374793308.088650138711230.597203613
#Sta/Elev= 30
8967.32651.053949060.30150.458129096.83249.111859201.021 47.56129266.91248.04235
9283.38446.862289349.09446.930829422.12445.495519442.37243.632599521.57542.49937
9641.52943.789099665.30942.933319716.68843.007319765.56541.411349836.833 42.9716
9884.13441.788969919.04142.258579953.94844.63108 9977.22 42.81349988.85633.40893
9997.484 32.4563   1000132.6555310012.1536.22394 10023.843.8648610068.2543.92426
10139.57 47.638610231.9349.2037610293.5348.7727510324.3249.7525710724.9752.73264
#Mann= 3 , 0 , 0
8967.326  0.0502       08967.326  0.0502       010724.97  0.0502       0
#XS Ineff= 2 , 0
       0 9950.77        10051.31       0
Bank Sta=8967.326,10724.97
Exp/Cntr=0.3,0.1

Type RM Length L Ch R = 1 ,6707.912,1348.051600,1348.051600,1348.051600
XS GIS Cut Line= 6
794723.176956265711608.841869495 794364.90538703711002.292012897
794204.709916754710811.301082054794095.526328553710750.971435408
 793811.70971933710715.494359255793449.890766617710761.038003651
#Sta/Elev= 30
9095.87143.777859192.21741.613089215.78140.196879296.61240.572519319.70741.62627
9342.80139.898539365.89640.080259423.63338.545569644.22336.978639743.53137.45928
9817.78336.965679833.58637.671859857.91536.897029921.26537.94046  9952.837.28218
9968.56838.500089976.04236.430769997.31427.242099999.55926.8039710013.9128.93884
 10024.838.0907810028.7240.2746210037.8639.0708210074.4137.6178910153.3338.39468
10206.5638.1313610377.8940.1566110498.82 40.896710549.2242.21464 10826.544.78449
#Mann= 3 , 0 , 0
9095.871  0.0428       09095.871  0.0428       0 10826.5  0.0428       0
#XS Ineff= 2 , 0
       0 9693.11        10027.84       0
Bank Sta=9095.871,10826.5
Exp/Cntr=0.3,0.1

Type RM Length L Ch R = 1 , 5359.86,472.503200,472.503200,472.503200
XS GIS Cut Line= 6
796132.443215347711739.766179638795943.909588113711320.300667756
795760.474515108711006.488952753795439.057641802710660.289155293
  795245.3034693710514.973525912794009.334631177710258.370999001
#Sta/Elev= 30
8857.131 54.94098938.55453.107559036.56746.995699101.99244.777859123.94542.09251
9256.45940.476459447.47935.747639575.183 36.04759586.89334.408859600.61229.06963
9610.31428.03334 9655.0331.275439707.52231.068579724.06327.645019740.76726.77416
9808.93526.122189865.49227.985369908.66827.528359964.09724.946659977.27820.11004
9992.22717.2552210007.6418.2331610030.0524.1510510038.1724.7848310230.2123.71529
10346.8826.6108810928.3231.4634811071.3129.9373711357.2830.3149911659.2534.34072
#Mann= 3 , 0 , 0
8857.131  0.0422       08857.131  0.0422       011659.25  0.0422       0
#XS Ineff= 2 , 0
       0                   10288       0
Bank Sta=8857.131,11659.25
Exp/Cntr=0.3,0.1

Type RM Length L Ch R = 1 ,4887.357,221.150100,221.150100,221.150100
XS GIS Cut Line= 6
796226.082465013711230.470226931795955.711523504710576.077708754
795736.672742791 710271.70286582795585.631076124710166.668143598
795290.492187235710056.425088042794454.815103901709704.081338042
#Sta/Elev= 30
9065.82440.431829251.974 35.5825 9304.3532.582739526.17827.954649580.27823.31649
9666.83722.580599688.47723.935289710.11720.708049731.75719.901629753.39622.46783
9775.14918.791839863.43318.6227710035.4514.3661410177.7218.2575810298.8717.11551
10355.7918.3875510366.4617.2309210398.49 19.348310473.2118.3899310494.5619.74637
10505.2318.2637410526.5819.5962810537.26 17.931410558.6119.6014710567.1618.07779
10579.9619.7099410652.4918.4744110665.6320.2014810678.23 18.647411555.74 24.2791
#Mann= 3 , 0 , 0
9065.824  0.0403       09065.824  0.0403       011555.74  0.0403       0
#XS Ineff= 2 , 0
       0 9941.78        10045.66       0
Bank Sta=9065.824,11555.74
Exp/Cntr=0.3,0.1

Type RM Length L Ch R = 2 ,4794.791,,,
Bridge Culvert--1,0,-1,-1, 0
Deck Dist Width WeirC Skew NumUp NumDn MinLoCord MaxHiCord MaxSubmerge Is_Ogee
19.575,182,2.6,0, 60, 60, , , 0.95, 0, 0,0,,
 9420.33 9438.59 9524.42 9545.88 9556.61 9588.79 9631.71 9739.00 9792.64 9835.58
 9878.47 9921.39 9932.12 9942.8410024.2810038.1910066.0010142.6510232.5610260.86
10294.2310349.8410482.1910545.8510673.1910786.5110832.3610874.8110896.0310906.64
10927.8710938.4810949.0910959.7010970.3110991.5311033.9811087.0411182.5411193.15
11235.6011288.6511299.2711309.8811331.1011352.3211362.9311373.5511384.1611405.38
11415.9911426.6011447.8311458.4411490.2711503.9011522.1111532.7211543.3311563.87
   28.86   28.25   26.19   26.13   25.89   25.97   25.40   24.65   24.56   24.81
   25.25   25.89   25.85   25.39   25.32   25.17   25.35   24.53   25.27   25.05
   24.48   23.81   22.83   22.07   21.65   21.83   21.63   21.67   21.85   21.74
   21.88   21.74   22.01   21.93   22.12   22.07   22.32   22.35   23.04   22.92
   23.22   23.28   23.44   23.37   23.60   23.50   23.65   23.56   23.73   23.62
   23.77   23.66   23.91   23.80   23.86   24.05   23.97   24.16   24.09   24.35
                                                                                
                                                                                
                                                                                
                                                                                
                                                                                
                                                                                
 9420.33 9438.59 9524.42 9545.88 9556.61 9588.79 9631.71 9739.00 9792.64 9835.58
 9878.47 9921.39 9932.12 9942.8410024.2810038.1910066.0010142.6510232.5610260.86
10294.2310349.8410482.1910545.8510673.1910786.5110832.3610874.8110896.0310906.64
10927.8710938.4810949.0910959.7010970.3110991.5311033.9811087.0411182.5411193.15
11235.6011288.6511299.2711309.8811331.1011352.3211362.9311373.5511384.1611405.38
11415.9911426.6011447.8311458.4411490.2711503.9011522.1111532.7211543.3311563.87
   28.86   28.25   26.19   26.13   25.89   25.97   25.40   24.65   24.56   24.81
   25.25   25.89   25.85   25.39   25.32   25.17   25.35   24.53   25.27   25.05
   24.48   23.81   22.83   22.07   21.65   21.83   21.63   21.67   21.85   21.74
   21.88   21.74   22.01   21.93   22.12   22.07   22.32   22.35   23.04   22.92
   23.22   23.28   23.44   23.37   23.60   23.50   23.65   23.56   23.73   23.62
   23.77   23.66   23.91   23.80   23.86   24.05   23.97   24.16   24.09   24.35
                                                                                
                                                                                
                                                                                
                                                                                
                                                                                
                                                                                
BR Coef=-1 , 0 , 0 ,, 0 ,,,0.8,-1,,0,
WSPro=,,,, 1 ,,,, 0 ,,,, 0 ,,,,-1 ,-1 ,-1 , 0 , 0 , 0 , 0 , 0
Multiple Barrel Culv=2,6,13,182,0.013,0.5,1,8,3,16,14,5,Culvert #1, 0, 19.575
 9948.00 9948.00 9974.00 9974.0010000.0010000.0010026.0010026.0010052.0010052.00
Culvert Bottom n=0.013
BC Design=,, 0 ,, 0 ,,,,,,

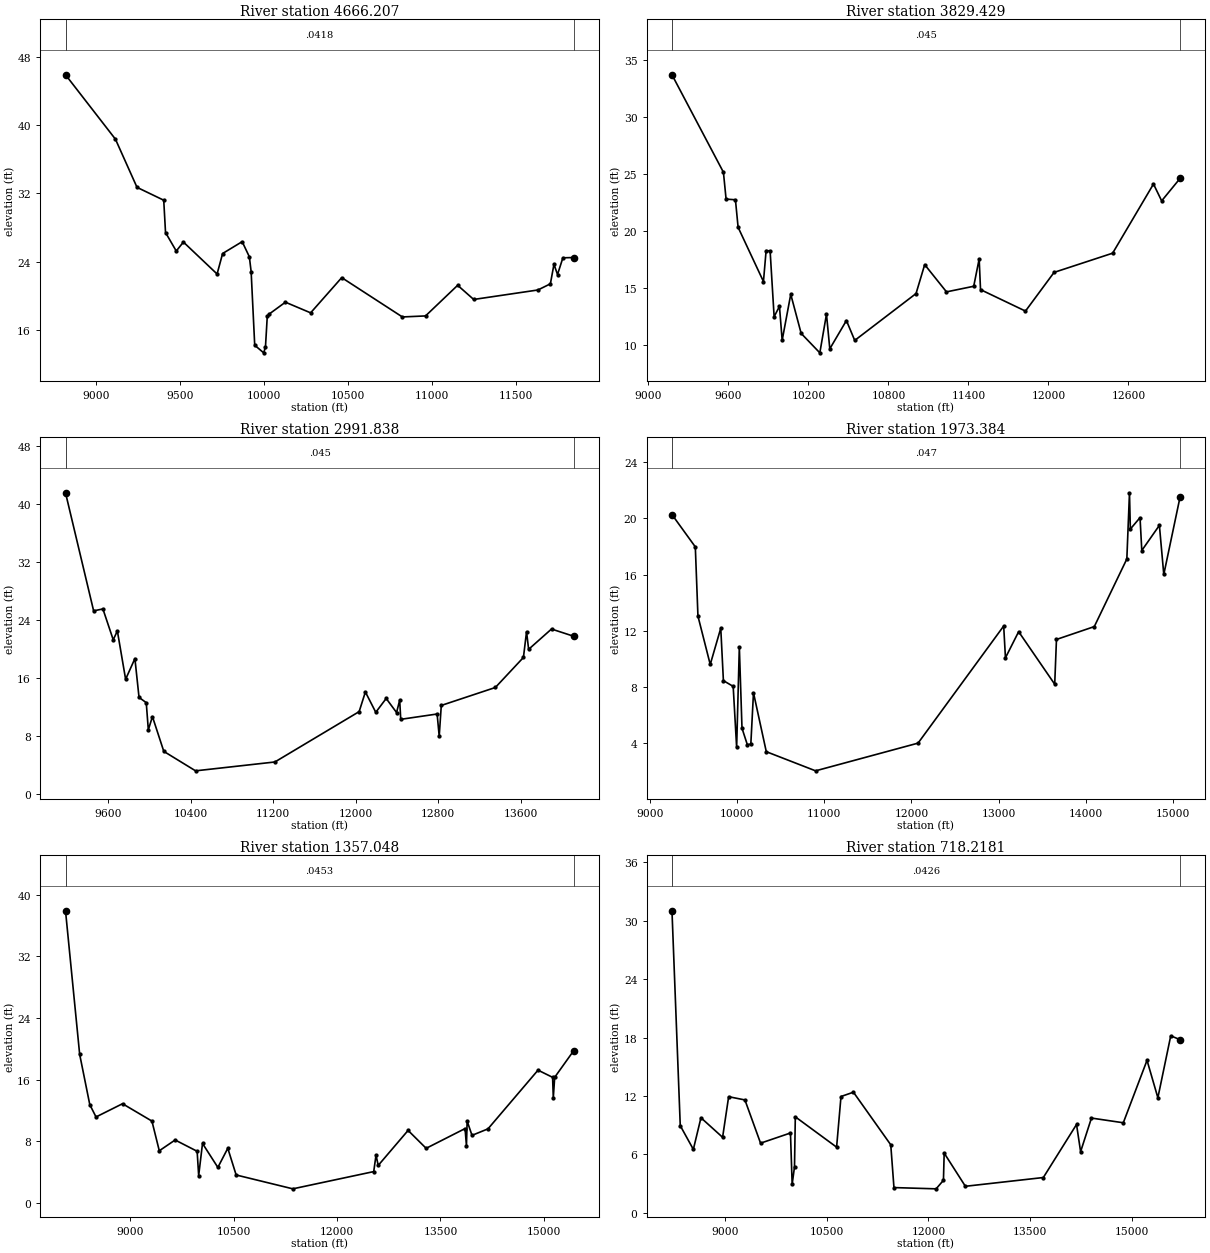
Type RM Length L Ch R = 1 ,4666.207,836.778000,836.778000,836.778000
XS GIS Cut Line= 6
796396.959180743711365.691738725796103.848255545710534.873679921
795988.813946486710224.987009346795887.251446515710145.559926003
795639.855613172709998.424509346794325.164580435709529.730470374
#Sta/Elev= 30
 8818.7445.877749116.03338.341269244.37432.708119403.46131.203329414.10727.42361
 9477.9825.257259520.56226.307729721.03822.57126    975424.969489870.373  26.355
 9913.0424.586859923.70722.85497 9945.0414.239089998.374 13.348310009.0414.03181
10019.7117.6138310030.3717.8758710127.7619.27334 10277.8 18.027210462.9422.14705
 10823.917.5473410961.9117.6663911153.0121.2493511248.5519.5929311630.7520.70138
11705.0621.42225 11726.323.7080211747.5322.5078911779.3824.46485 11842.924.49849
#Mann= 3 , 0 , 0
 8818.74  0.0418       0 8818.74  0.0418       0 11842.9  0.0418       0
#XS Ineff= 2 , 0
       09837.076        10014.75       0
Bank Sta=8818.74,11842.9
Exp/Cntr=0.3,0.1

Type RM Length L Ch R = 1 ,3829.429,837.590400,837.590400,837.590400
XS GIS Cut Line= 6
796872.355276287711138.604726762796828.026742309710319.417424411
 796740.51071614710092.950495362796469.677382797709891.561606467
          796045 709684.43295674794150.232938319709294.339384258
#Sta/Elev= 30
9177.53133.717829563.18925.154149583.21222.791339653.29222.732489673.31120.31266
9863.33215.548439883.332 18.26699913.33318.235779943.33312.456229983.33613.36614
10003.6610.3852610067.9814.4262610146.0310.9881610285.969.28053210335.8112.67493
10360.739.63334410485.3512.1195210547.6610.37219 11007.214.4898511072.1317.03178
11235.4814.6382511439.6815.1312611480.5217.5323611490.7314.8364711827.6512.94946
12042.0516.3508612481.0718.0390612787.3624.1172312848.62 22.636112986.2224.60488
#Mann= 3 , 0 , 0
9177.531   0.045       09177.531   0.045       012986.22   0.045       0
#XS Ineff= 2 , 0
       09890.912        10080.84       0
Bank Sta=9177.531,12986.22
Exp/Cntr=0.3,0.1

Type RM Length L Ch R = 1 ,2991.838,1018.454500,1018.454500,1018.454500
XS GIS Cut Line= 6
797669.619193286711127.351251066797664.109422177  709989.1349141
797620.706644386709873.538849294797531.296922207709804.239080772
  796340.7055794709446.444791242 794053.01071611709162.394939795
#Sta/Elev= 30
9187.02341.553639459.55125.276959549.55525.540749649.56521.28393 9689.57 22.5132
9769.57915.848839859.58918.699689899.59313.345689969.59312.621279989.5938.879111
10029.5910.6981710139.595.90666510447.37 3.2238611216.024.44506512032.6911.38575
12093.1514.0979912193.9211.2908212294.6813.2000312395.4511.2593112425.6812.97899
12435.76 10.324112788.4511.05852 12808.67.99257812828.7512.2384813352.7514.71342
13624.82 18.852913655.0522.40985 13675.2 19.973213896.8922.7725514110.5121.78172
#Mann= 3 , 0 , 0
9187.023   0.045       09187.023   0.045       014110.51   0.045       0
#XS Ineff= 2 , 0
       09862.551         10403.2       0
Bank Sta=9187.023,14110.51
Exp/Cntr=0.3,0.1

Type RM Length L Ch R = 1 ,1973.384,616.336000,616.336000,616.336000
XS GIS Cut Line= 6
798768.276088864711180.975191876798637.633727729710235.662691876
798557.338588834710094.603664085798398.484422177710008.955515951
          796365709357.228145003 793990.51071611709030.450495362
#Sta/Elev= 30
9251.74220.277029519.60717.97313 9549.8213.033619690.8149.5823139811.66712.17416
 9841.888.4310629954.1348.0208559993.8143.66699410024.7110.8297710055.335.037135
10116.133.86804910156.673.90373610187.077.567168   103343.36275210899.641.996195
12075.763.97348313058.3112.32775 13078.510.0575513229.9111.9246113643.788.175057
13663.9611.3692514098.0212.28624 14471.517.1094814501.7921.8325914511.8819.24641
14622.92 20.058714643.1117.7147914844.9919.5090814895.4616.0066915081.6921.51449
#Mann= 3 , 0 , 0
9251.742   0.047       09251.742   0.047       015081.69   0.047       0
#XS Ineff= 2 , 0
       09798.446        11001.94       0
Bank Sta=9251.742,15081.69
Exp/Cntr=0.3,0.1

Type RM Length L Ch R = 1 ,1357.048,638.829800,638.829800,638.829800
XS GIS Cut Line= 5
800916.713588834711119.198571503799953.168752909710613.257035017
798729.742331743710020.966385901796442.549310565709168.280468196
793983.566271663708870.728273153
#Sta/Elev= 30
8063.729 37.9106 8268.9719.287868415.80112.764138506.15911.167878890.18112.88552
9316.64710.632299423.4186.782915 9652.918.1807519972.1526.7166089994.3723.560911
10049.92 7.7309410272.544.62374810416.567.10933510537.693.64331811359.46 1.84572
12532.244.08319812565.436.20843312597.454.88460613030.37 9.4243113292.277.099792
13856.359.662259 13876.57.44608113886.5710.6349613957.088.78197714188.769.625622
14914.0117.2402315125.5416.3091115135.6113.6609715155.7616.3125515429.1719.73744
#Mann= 3 , 0 , 0
8063.729  0.0453       08063.729  0.0453       015429.17  0.0453       0
#XS Ineff= 2 , 0
       0 9369.83        11137.97       0
Bank Sta=8063.729,15429.17
Exp/Cntr=0.3,0.1

Type RM Length L Ch R = 1 ,718.2181,718.218100,718.218100,718.218100
XS GIS Cut Line= 6
800987.664580435710678.167970374800322.536820173710191.522610903
799586.470493734709741.828818604799011.068563581709376.947110295
797324.028105021708690.005661666794018.288493901708697.117162019
#Sta/Elev= 30
8216.944 31.02728339.2398.9383448532.2696.5045718644.5899.7547888963.9137.745158
9053.15511.920329293.27311.585249524.0677.1419239965.2098.1892759990.1962.919631
 10024.8 4.7096110036.729.85022710645.956.73376610710.7411.9391710894.2912.38072
11444.956.97429611492.142.57818612114.382.44885812222.353.32809312233.156.121366
12545.982.71051113695.983.61139214185.989.06501314245.986.26924814405.98 9.72306
14875.989.23933115225.9815.6562515385.9911.8108215575.9918.17737 15712.717.78222
#Mann= 3 , 0 , 0
8216.944  0.0426       08216.944  0.0426       0 15712.7  0.0426       0
#XS Ineff= 2 , 0
       09410.465        10686.66       0
Bank Sta=8216.944,15712.7
Exp/Cntr=0.3,0.1

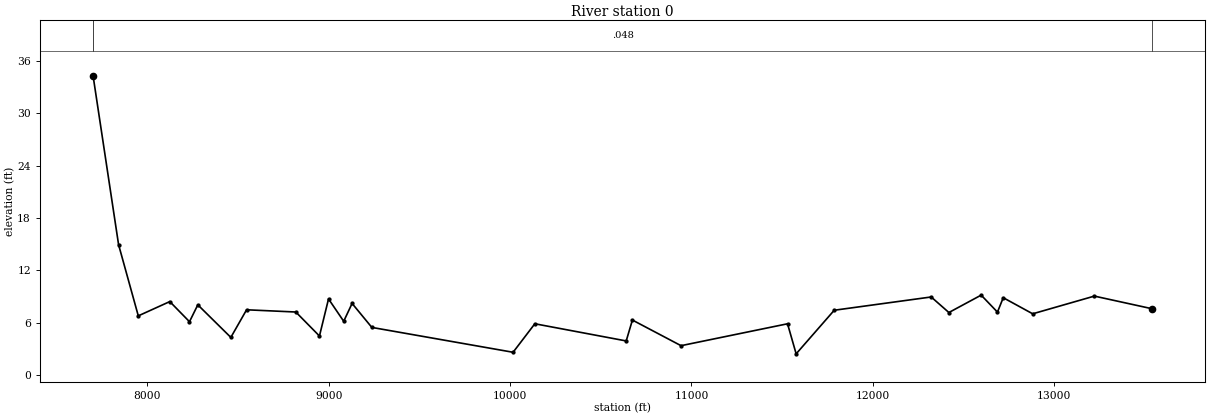
Type RM Length L Ch R = 1 ,       0,0.000000,0.000000,0.000000
XS GIS Cut Line= 6
801169.956247091710714.626303688800669.956247091709532.334637046
799846.029658288709062.244677156799694.834945232709065.557313576
798401.520582795708184.505398825796957.076138318706969.227621049
#Sta/Elev= 30
7700.90934.324887841.65114.931117950.2266.7683888123.9468.4078528232.5216.096584
8278.449 8.033478460.5284.2962658547.388 7.466028818.8257.2099178949.1154.454627
8999.1778.7114579082.8456.1459929129.111 8.194059237.9775.44201110016.81 2.58877
10136.735.86114310640.58 3.8895210674.696.287084 10942.93.34590511530.095.859473
11577.582.40924811787.627.41356512322.218.93593712419.777.15226812597.699.147979
12687.597.19893112719.49 8.8512812881.887.00419213221.919.03614513542.177.575785
#Mann= 3 , 0 , 0
7700.909   0.048       07700.909   0.048       013542.17   0.048       0
#XS Ineff= 2 , 0
       09836.674        10652.43       0
Bank Sta=7700.909,13542.17
Exp/Cntr=0.3,0.1